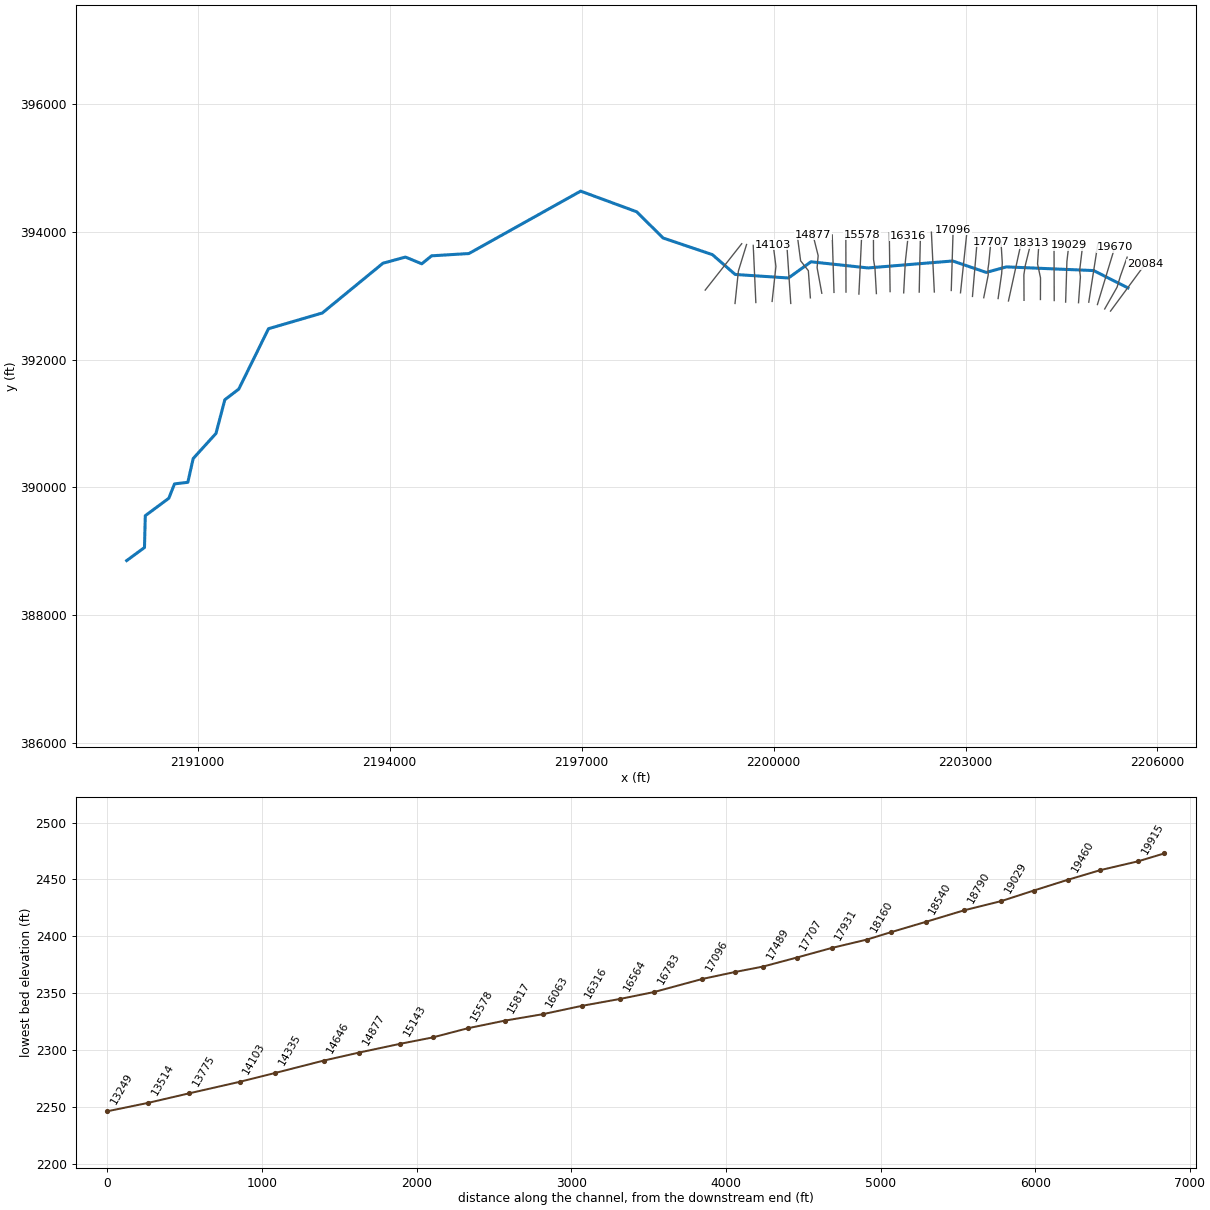
--- OLDHMRN.prj (project) ---

Proj Title=OLDHMRN
Current Plan=p01
Default Exp/Contr=0,0
English Units
Geom File=g01
Flow File=f01
Plan File=p01
Background Map Layer=Inundation Boundary (01pct Value_0)
BEGIN DESCRIPTION:
----------MODEL BY WOOD PLC 2021----------
Stream Name: Oldham Run
Flood Zone: Enhanced Approximate
Pocahontas County, WV
HEC-RAS Version: RAS 6.1
Vertical Datum: NAVD88
Projection: NAD 1983 StatePlane West Virginia S FIPS 4702 (US Feet)
Terrain: 1-meter LIDAR (FEMA Region III 3DEP collected 2016-2018)
Land Use: 2019 NLCD
Hydrologic Method:
WV SIR2010-5033 regression equations
Model Notes:
Coincident peak with Perry Run (PERRYRN).
END DESCRIPTION:
DSS File=dss
DSS Export Rating Curves= 0
DSS Export Rating Curve Sorted= 0
DSS Export Volume Flow Curves= 0
DXF OffsetX= 0
DXF OffsetY= 0
DXF ScaleX= 0
DXF ScaleY= 0

--- OLDHMRN.p01 (plan) ---

Plan Title=Floodplain
Program Version=6.10
Short Identifier=Floodplain
Geom File=g01
Flow File=f01
Subcritical Flow
K Sum by GR= 0
Std Step Tol= 0.01
Critical Tol= 0.01
Num of Std Step Trials= 20
Max Error Tol= 0.3
Flow Tol Ratio= 0.001
Split Flow NTrial= 30
Split Flow Tol= 0.02
Split Flow Ratio= 0.02
Log Output Level= 0
Friction Slope Method= 1
Unsteady Friction Slope Method= 2
Unsteady Bridges Friction Slope Method= 1
Parabolic Critical Depth
Global Vel Dist= 0 , 0 , 0
Global Log Level= 0
CheckData=True
Encroach Param=-1 ,0,0, 0
Computation Interval=0.1SEC
Output Interval=1SEC
Instantaneous Interval=Max Profile
Mapping Interval=1HOUR
Computation Time Step Use Courant=        0
Computation Time Step Use Time Series=    0
Computation Time Step Count To Double=0
Computation Time Step Max Doubling=0
Computation Time Step Max Halving=0
Computation Time Step Residence Courant=0
Run HTab= 0
Run UNet= 0
Run Sediment= 0
Run PostProcess= 0
Run WQNet= 0
Run RASMapper=-1
UNET Theta= 0
UNET Theta Warmup= 0
UNET ZTol= 0
UNET ZSATol= 0
UNET MxIter= 0
UNET Max Iter WO Improvement= 0
UNET MaxInSteps= 0
UNET DtIC= 0
UNET DtMin= 0
UNET MaxCRTS= 0
UNET WFStab= 0
UNET SFStab= 0
UNET WFX= 1
UNET SFX= 1
UNET Gravity=32.174
UNET 1D Methodology=Finite Difference
UNET DSS MLevel= 1
UNET Pardiso=0
UNET DZMax Abort= 0
UNET Use Existing IB Tables= 0
UNET Froude Reduction=False
UNET Froude Limit= 0
UNET Froude Power= 0
UNET D1 Cores= 0
UNET WindReference=Eulerian
UNET WindDragFormulation=Hsu (1988)
UNET D2 Coriolis=0
UNET D2 Cores= 0
UNET D2 Theta= 1
UNET D2 Theta Warmup= 1
UNET D2 Z Tol= 0.01
UNET D2 Volume Tol= 0.01
UNET D2 Max Iterations= 20
UNET D2 Equation= 0
UNET D2 RampUpFraction=0.1
UNET D2 TimeSlices= 1
UNET D2 Turbulence Formulation=Non-Conservative (original)
UNET D2 Eddy Viscosity=0.3
UNET D2 Transverse Eddy Viscosity=0.1
UNET D2 Smagorinsky Mixing=0
UNET D2 BCVolumeCheck=0
UNET D2 Cores=0
UNET D2 SolverType=PARDISO (Direct)
UNET D2 Minimum Iterations= 2147483647
UNET D2 Maximum Iterations= 2147483647
UNET D2 Restart Number= 10
UNET D2 Relaxation Coeff=1.3
UNET D2 SOR Precondition Iterations= 10
UNET D2 ILUT Maximum Fill= 8
UNET D2 ILUT Tolerance=1E-08
UNET D1D2 MaxIter= 0
UNET D1D2 ZTol=0.01
UNET D1D2 QTol=0.1
UNET D1D2 MinQTol=1
DSS File=dss
Write IC File= 0
Write IC File at Fixed DateTime=0
Write IC File at Sim End=0
Echo Input=False
Echo Parameters=False
Echo Output=False
Write Detailed= 0
HDF Write Warmup=0
HDF Write Time Slices=0
HDF Flush=0
HDF Compression= 1
HDF Chunk Size= 1
HDF Spatial Parts= 1
HDF Use Max Rows=0
HDF Fixed Rows= 1
Calibration Method= 0
Calibration Iterations= 20
Calibration Max Change=0.05
Calibration Tolerance=0.2
Calibration Maximum=1.5
Calibration Minimum=0.5
Calibration Optimization Method= 1
WQ AD Non Conservative
WQ ULTIMATE=-1
WQ Max Comp Step=1HOUR
WQ Output Interval=15MIN
WQ Output Selected Increments= 0
WQ Output face flow=0
WQ Output face velocity=0
WQ Output face area=0
WQ Output face dispersion=0
WQ Output cell volume=0
WQ Output cell surface area=0
WQ Output cell continuity=0
WQ Output cumulative cell continuity=0
WQ Output face conc=0
WQ Output face dconc_dx=0
WQ Output face courant=0
WQ Output face peclet=0
WQ Output face adv mass=0
WQ Output face disp mass=0
WQ Output cell mass=0
WQ Output cell source sink temp=0
WQ Output nsm pathways=0
WQ Output nsm derived pathways=0
WQ Create Restart=0
WQ Fixed Restart=0
WQ System Summary=0
WQ Write To DSS=0
Sorting and Armoring Iterations= 10
XS Update Threshold= 0.02
Bed Roughness Predictor= 0
Hydraulics Update Threshold= 0.02
Energy Slope Method= 1
Volume Change Method= 1
Sediment Retention Method= 0
Sediment TS Multiplier= 1
Warm Up Method= 0
XS Weighting Method= 0
Number of US Weighted Cross Sections= 1
Number of DS Weighted Cross Sections= 1
Upstream XS Weight=0
Main XS Weight=1
Downstream XS Weight=0
Number of DS XS's Weighted with US Boundary= 1
Upstream Boundary Weight= 1
Weight of XSs Associated with US Boundary= 0
Number of US XS's Weighted with DS Boundary= 1
Downstream Boundary Weight= 0.5
Weight of XSs Associated with DS Boundary= 0.5
Percentile Method= 0
Sediment Output Level= 3
Mass or Volume Output= 0
Output Increment Type= 1
Profile and TS Output Increment= 1
Transport Output Increment 1
XS Output Flag= 0
XS Output Increment= 10
Read HDF5 Sediment Hotstart= 0
Sediment Hotstart Type= 0
Write Gradation File= 0
Read Gradation Hotstart= 0
Write HDF5 File= 1
Write Binary Output= 1
Write DSS Sediment File= 0
DSS Sediment Output Type= 1
SV Curve= 0
Specific Gage Flag= 0
Subcell Erosion Methods= 0
Subcell Deposition Methods= 0
Advection Scheme= 1
Matrix Solver= 0
Implicit Weighting Factor= 1
Maximum Outer Loop Convergence Iterations= 5
Convergence Maximum Absolute= 0.001
Convergence RMSE= 0.0001
Grain Fractions Max Abs Error= 0.001
Max Subgrid Regions= 1
Max Subgrid Length Scale= 3.402823E+38
Initial Layer Thickness= 3.402823E+38
Min Layer Thickness= 3.402823E+38
Max Layer Thickness= 3.402823E+38
Number of Layers= 5

--- OLDHMRN.f01 (steady flow) ---

Flow Title=Flow
Program Version=6.00
Number of Profiles= 6
Profile Names=01pct,10pct,04pct,02pct,0_2pct,01plus
River Rch & RM=OLDHMRN,Main,20084
     681     362     480     577     948    1010
River Rch & RM=OLDHMRN,Main,13514
     759     405     536     644    1050    1120
River Rch & RM=OLDHMRN,Main,8103
    1160     628     825     985    1590    1710
River Rch & RM=OLDHMRN,Main,3030
    1520     833    1090    1300    2080    2250
Boundary for River Rch & Prof#=OLDHMRN,Main            , 1
Up Type= 0
Dn Type= 3
Dn Slope=0.00525
Boundary for River Rch & Prof#=OLDHMRN,Main            , 2
Up Type= 0
Dn Type= 3
Dn Slope=0.00525
Boundary for River Rch & Prof#=OLDHMRN,Main            , 3
Up Type= 0
Dn Type= 3
Dn Slope=0.00525
Boundary for River Rch & Prof#=OLDHMRN,Main            , 4
Up Type= 0
Dn Type= 3
Dn Slope=0.00525
Boundary for River Rch & Prof#=OLDHMRN,Main            , 5
Up Type= 0
Dn Type= 3
Dn Slope=0.00525
Boundary for River Rch & Prof#=OLDHMRN,Main            , 6
Up Type= 0
Dn Type= 3
Dn Slope=0.00525
DSS Import GetInterval= 0
DSS Import GetPeak= 0
DSS Import FillOption= 0

--- OLDHMRN.g01 (geometry) ---

Geom Title=Geometry
Program Version=6.10

River Reach=OLDHMRN         ,Main
Reach XY= 30
2205537.68737782393121.395459275 2205001.7983281393392.142992598
2203637.25237782393449.6994592752203324.18937782393363.055459275
2202798.39037782393542.1944592752201475.84237782393433.344459275
2200584.54637782393529.4444592752200231.96926695393275.906081451
2199400.08637782393331.2424592752199043.55994235  393641.3604237
2198274.00537782393901.5544592752197859.44537782394312.197459275
2196984.91237782394634.5574592752195238.68237782393658.423459275
2194655.83937782393623.0534592752194502.05037782393498.056459275
2194246.95537782393603.1364592752193895.33737782393506.884459275
2192947.70738593392728.6724428822192106.77688646392482.448634263
2191642.19987948391538.2565212422191424.11037782391371.347459275
2191285.83737782390844.3754592752190929.42537782390451.735459275
2190846.18316921390079.9619283342190637.94637782390055.444459275
2190548.65737782389830.4614592752190181.31637782389558.009459275
2190168.62393374389060.0963634252189890.85937782388855.950459275

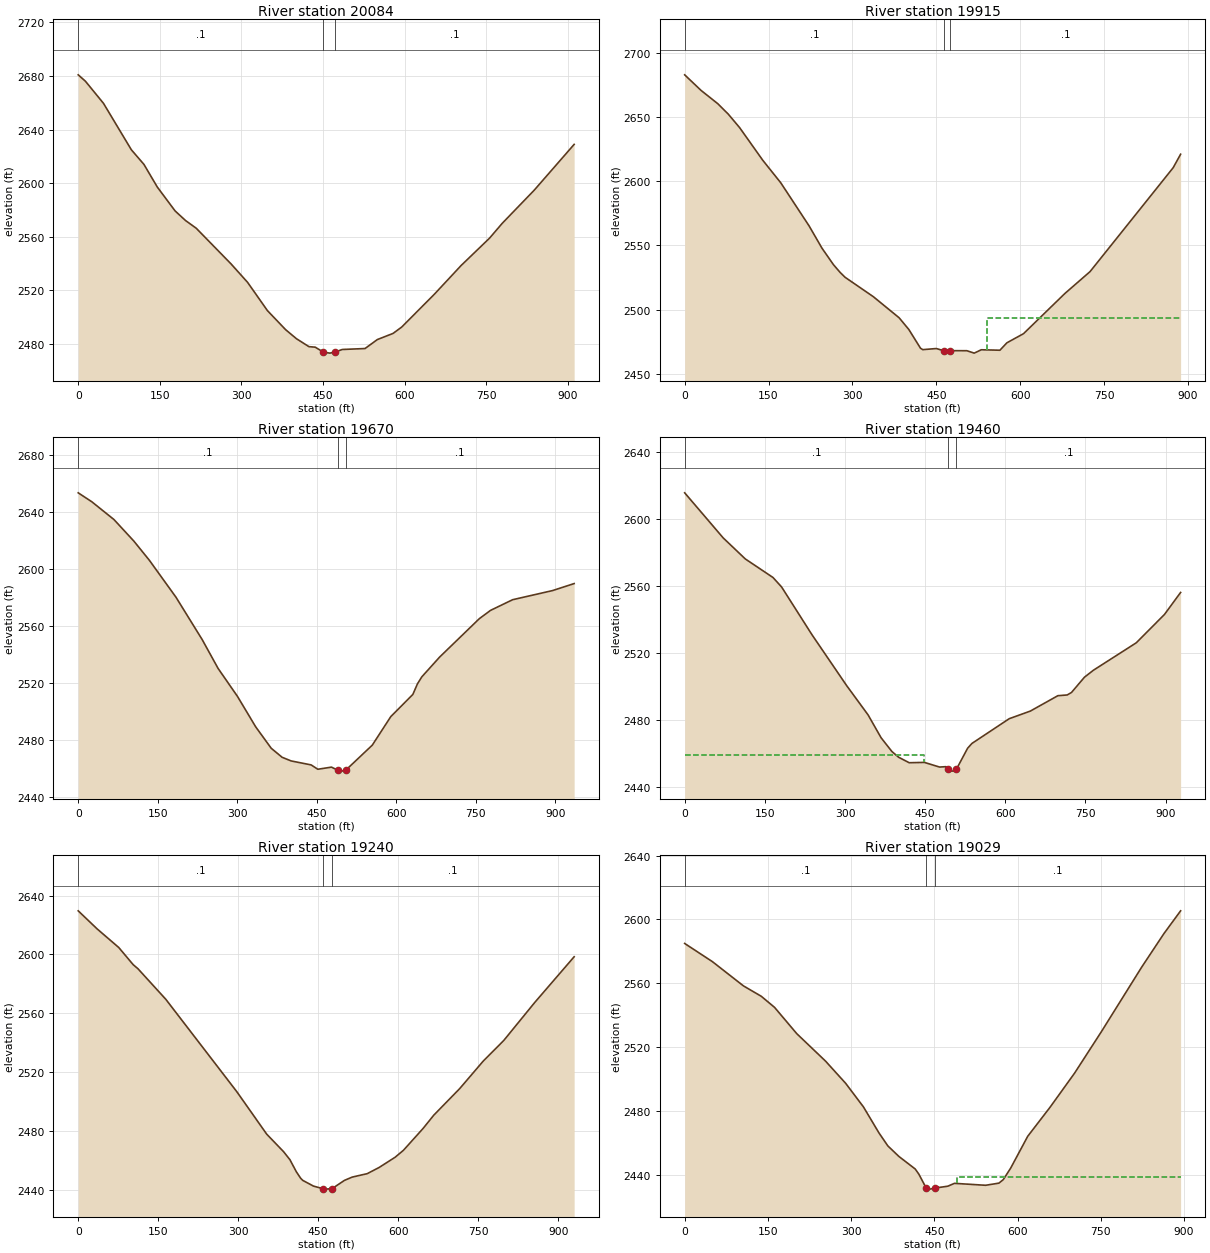
Type RM Length L Ch R = 1 ,20084   ,166.1,168.6,174.7
XS GIS Cut Line= 2
 2205266.0041647392758.505980887 2205806.3481647393492.274980887
#Sta/Elev= 30
       0 2680.86    13.3 2676.06    46.4 2659.58    97.7 2624.83   120.8 2613.92
   145.3 2597.03     178 2579.17   197.1 2572.02   216.9  2566.2     281 2539.49
   311.3 2525.75   347.7 2504.66   381.1 2490.43   401.1 2483.64     424 2477.73
   435.5 2477.34   450.72473.593   462.4 2472.89   472.6 2473.76   485.2 2475.61
     527 2476.32   549.7 2483.03   578.5 2487.61   594.5  2492.4   654.1 2516.76
   703.7  2538.4   755.9 2558.84   779.4    2570   837.9 2594.64   911.3 2628.88
#Mann= 3 ,-1,0
       0      .1       0   450.7    .045       0   472.6      .1       0
Bank Sta=450.7,472.6
XS Rating Curve= 0 ,0
Exp/Cntr=0.3,0.1

Type RM Length L Ch R = 1 ,19915   ,243.9,244.5,243.6
XS GIS Cut Line= 4
2205175.01323625392791.7738076582205367.90357229393131.523831365
2205421.84635209393310.6675088172205525.72293814393601.694025462
#Sta/Elev= 30
       0 2683.11    29.2 2670.99    59.1 2660.62    78.2 2652.33    98.2 2641.95
   139.6 2616.48   171.8 2598.89   222.4  2565.3   245.4 2547.94   265.9 2535.07
   277.6 2529.12   286.8 2525.16   337.4    2510   383.4 2493.58   400.8 2484.44
   421.7  2469.8   425.8  2468.7     450 2469.56   463.4 2467.82   474.9  2467.9
   504.6 2467.86   517.7 2465.98   530.4  2468.6   563.7 2468.24   576.2 2474.04
   605.9 2481.16   679.9 2512.53   724.8 2529.55   873.5 2610.65   886.8 2621.16
#Mann= 3 ,-1,0
       0      .1       0   463.4    .045       0   474.9      .1       0
#XS Ineff= 2 , 0
                          540.71         2493.74
Permanent Ineff=
       F       F
Bank Sta=463.4,474.9
XS Rating Curve= 0 ,0
Exp/Cntr(USF)=0,0
Exp/Cntr=0.3,0.1

Type RM Length L Ch R = 1 ,19670   ,209.3,210.7,212.6
XS GIS Cut Line= 2
 2205061.1718091392860.584214108 2205332.0098091393756.205214108
#Sta/Elev= 30
       0 2653.71    25.7 2647.42    67.5 2634.93   105.1 2619.76   134.2 2606.36
   184.5 2580.36   233.9 2550.62   263.9 2530.38   300.6 2510.65   334.9  2489.3
   364.2 2474.27   384.7 2467.95   401.8 2465.37   439.4  2462.6   452.1 2459.54
   477.8 2461.02   489.6 2458.88   497.9 2458.22   505.6 2459.17   554.8 2476.45
   589.8 2496.53   631.4 2512.11     640  2519.5   648.3 2524.45   681.8  2538.3
   756.6 2565.25   777.9 2571.13   819.7 2578.64   894.8 2585.03   935.7 2589.96
#Mann= 3 ,-1,0
       0      .1       0   489.6    .045       0   505.6      .1       0
Bank Sta=489.6,505.6
XS Rating Curve= 0 ,0
Exp/Cntr=0.3,0.1

Type RM Length L Ch R = 1 ,19460   ,216.8,220,223.5
XS GIS Cut Line= 2
2204925.89255084392897.9432209462205068.71414583393815.008199311
#Sta/Elev= 30
       0 2615.79    72.1 2588.88   113.4 2576.35   165.2 2565.28   181.4  2559.6
   238.1 2531.17   302.8 2500.89   343.3 2483.23   367.6 2469.61   387.9 2461.39
   400.6 2457.96   420.2 2454.72   448.6 2454.92   476.9 2452.14   489.1 2452.37
   493.42450.802   501.2 2449.71   508.62450.876   529.5 2463.38   537.6 2466.24
   607.3 2480.99   646.9 2485.55   698.4 2494.73   715.8 2495.16   723.9 2496.65
   748.1 2505.74   764.9 2509.92   845.1 2526.29   897.8 2543.17   928.1 2556.34
#Mann= 3 ,-1,0
       0      .1       0   493.4    .045       0   508.6      .1       0
#XS Ineff= 2 , 0
          447.33 2459.18
Permanent Ineff=
       F       F
Bank Sta=493.4,508.6
XS Rating Curve= 0 ,0
Exp/Cntr(USF)=0,0
Exp/Cntr=0.3,0.1

Type RM Length L Ch R = 1 ,19240   ,212.7,210.6,208.8
XS GIS Cut Line= 4
2204765.63069129392889.4256000342204795.30559819393294.743011496
 2204783.3211901393393.8141184092204833.74569129393814.452600033
#Sta/Elev= 30
       0  2629.6    35.8 2617.19      76 2604.66     103    2593   112.1 2590.17
   164.2 2569.42   297.4 2506.53   353.4 2477.66   384.8 2465.82   396.8 2460.36
   408.9 2452.11   416.9 2447.73   420.9 2446.23   441.1 2442.32   458.1 2440.63
   465.2 2440.26   476.1 2440.63   499.1  2446.2   513.6 2448.44   541.8 2450.78
     564 2454.96   594.2 2461.96   609.8  2466.7   646.6 2481.55   666.7  2490.6
   715.1  2508.6   759.4 2527.39   797.8 2541.38     856 2567.29   929.8 2598.35
#Mann= 3 ,-1,0
       0      .1       0   458.1    .045       0   476.1      .1       0
Bank Sta=458.1,476.1
XS Rating Curve= 0 ,0
Exp/Cntr=0.3,0.1

Type RM Length L Ch R = 1 ,19029   ,233.6,238.7,238.8
XS GIS Cut Line= 3
2204564.40600224392899.2575443842204584.38001573393536.029094462
 2204613.9415557393790.897506601
#Sta/Elev= 30
       0 2584.97    49.9 2573.58     106 2558.35     138 2551.86     162 2544.89
     202 2528.42   253.9 2511.19   290.1  2497.3   322.1 2482.54   350.1 2466.22
   366.1 2458.07   386.1 2451.44   415.4 2443.59   422.1  2440.3   435.22431.626
   442.1 2430.97   450.22431.594   474.2 2432.81   486.2  2434.6   542.2 2433.38
   566.2 2434.72   574.2 2436.95   587.6 2444.23   618.2  2464.1   658.4 2482.28
   702.7 2503.72     751 2529.71   823.5 2570.11   863.7 2591.18   893.7 2605.42
#Mann= 3 ,-1,0
       0      .1       0   435.2    .045       0   450.2      .1       0
#XS Ineff= 2 , 0
                          490.21         2438.41
Permanent Ineff=
       F       F
Bank Sta=435.2,450.2
XS Rating Curve= 0 ,0
Exp/Cntr(USF)=0,0
Exp/Cntr=0.3,0.1

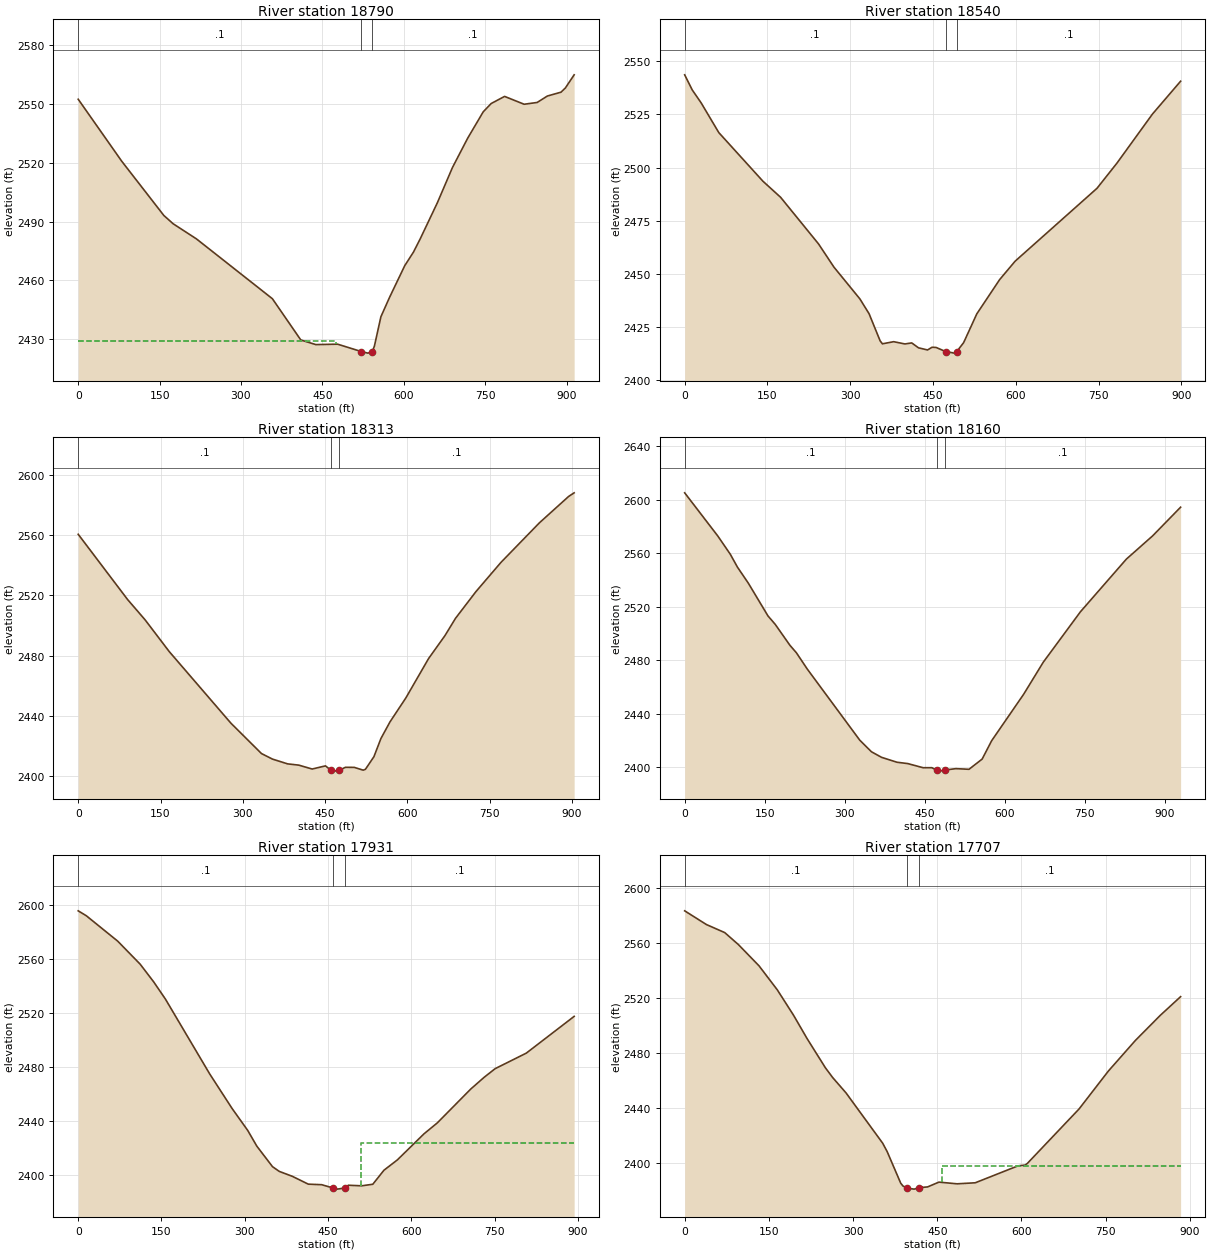
Type RM Length L Ch R = 1 ,18790   ,245.4,250,251.6
XS GIS Cut Line= 2
2204385.91014357392923.3073697392204382.96201791393837.382369739
#Sta/Elev= 30
       0 2552.34    80.4 2520.68   157.9 2493.08     175 2488.87   217.9 2481.17
   357.9 2450.67   410.3 2429.64   437.9 2427.29   478.1  2427.5   521.8 2423.75
   533.9 2422.94   541.9 2423.67   545.9 2426.47   557.9 2441.48     574 2451.45
   601.9 2467.54   617.9 2474.42   630.2 2481.09   661.9 2499.53   689.9 2517.59
   717.9  2532.5   746.5 2545.92   761.2 2550.16   785.9 2553.78   821.9 2549.79
   845.9 2550.69   864.8 2553.98   889.9 2555.94   897.9 2558.08   914.1 2564.78
#Mann= 3 ,-1,0
       0      .1       0   521.8    .045       0   541.9      .1       0
#XS Ineff= 2 , 0
          474.31 2429.33
Permanent Ineff=
       F       F
Bank Sta=521.8,541.9
XS Rating Curve= 0 ,0
Exp/Cntr=0.3,0.1

Type RM Length L Ch R = 1 ,18540   ,232,227.3,222.8
XS GIS Cut Line= 4
2204170.36991845392939.3335821682204171.87330366393277.595254516
2204125.26836214393497.0894952392204147.81914029393832.344397165
#Sta/Elev= 30
       0  2543.6    13.8 2536.45    29.8 2530.43    61.8 2516.44   141.8 2493.56
   173.8 2486.01   242.6 2464.06   270.5 2453.15   317.5 2438.21   334.2 2431.21
   354.2 2418.47   358.3 2417.08   378.7 2418.08   399.2 2417.01   411.4 2417.51
   423.7  2415.2   440.1 2414.19   448.2 2415.46   455.7 2415.36   472.8 2413.45
   489.1  2412.7   492.8 2413.36   505.5 2417.63   529.4 2431.18   570.8  2447.3
   598.8 2455.94   747.2 2490.23   783.1 2501.99   847.6 2525.12   898.7  2540.6
#Mann= 3 ,-1,0
       0      .1       0   472.8    .045       0   492.8      .1       0
Bank Sta=472.8,492.8
XS Rating Curve= 0 ,0
Exp/Cntr(USF)=0,0
Exp/Cntr=0.3,0.1

Type RM Length L Ch R = 1 ,18313   ,152.5,152.6,150.6
XS GIS Cut Line= 4
2203914.23634182392927.221163271 2203911.8394602393325.103512002
2203934.21035531393473.7101723712204019.69913305393818.861125488
#Sta/Elev= 30
       0 2560.45      90 2517.22     122 2503.72     166 2482.69   278.3  2435.3
     334 2415.18     354 2411.51   381.7 2408.34     402 2407.51   426.3 2404.93
   450.6 2407.02  460.912404.068   466.7 2403.54   475.6 2404.08     487 2406.07
   503.1 2406.02   519.3 2404.19   523.4 2404.74   538.9  2413.1   551.7 2425.17
   568.2 2436.17   597.1 2452.04   638.5 2478.11   668.3 2493.28   687.7 2504.83
   724.8 2522.46   770.6  2541.9   840.5 2568.04   893.8 2585.53   903.8 2587.91
#Mann= 3 ,-1,0
       0      .1       0  460.91    .045       0   475.6      .1       0
Bank Sta=460.91,475.6
XS Rating Curve= 0 ,0
Exp/Cntr(USF)=0,0
Exp/Cntr=0.3,0.1

Type RM Length L Ch R = 1 ,18160   ,226.3,229.2,230.2
XS GIS Cut Line= 2
2203670.84513949392916.6465975552203869.31213949393824.534597556
#Sta/Elev= 30
       0    2605      62  2572.8    85.6 2559.07    98.8 2549.56   119.3 2537.52
   156.1 2513.06   169.6 2506.81   197.1  2491.2   209.4 2485.52   229.8 2473.35
   328.1 2420.28     350 2411.61     369 2407.45   397.7 2403.81   418.2 2402.78
   446.8  2399.7   463.2 2399.72     472 2397.88   478.7 2397.16   487.8    2398
   508.3 2399.01   532.8 2398.53   557.4 2406.16   575.3 2419.92   635.2 2454.58
     672 2478.54   741.6 2516.18   827.6 2555.48   876.8 2572.84   929.3 2594.28
#Mann= 3 ,-1,0
       0      .1       0     472    .045       0   487.8      .1       0
Bank Sta=472,487.8
XS Rating Curve= 0 ,0
Exp/Cntr=0.3,0.1

Type RM Length L Ch R = 1 ,17931   ,222,224.7,225.3
XS GIS Cut Line= 4
2203509.02682401392954.6510418782203564.88382213393346.003875936
2203574.44705239 393510.809033872203554.12838032393843.151701244
#Sta/Elev= 30
       0 2595.73    14.7 2592.05    71.2 2573.27   111.6 2556.24     136 2543.12
   157.1 2530.41   236.9 2474.99   277.3 2449.37   305.4 2433.17   321.8 2421.54
     350 2406.37   362.1 2402.88   385.8  2399.2   414.5 2393.42   438.6 2393.02
     459 2390.59   466.6 2389.74   480.3 2390.58   486.6 2392.62   510.7 2392.19
   530.7 2393.35   550.8 2403.74   574.8 2411.33   622.9 2430.66   646.9 2438.77
     707 2463.76   731.2 2472.49   751.1 2478.91   807.2  2490.4   893.4  2517.6
#Mann= 3 ,-1,0
       0      .1       0     459    .045       0   480.3      .1       0
#XS Ineff= 2 , 0
                          509.98         2423.66
Permanent Ineff=
       F       F
Bank Sta=459,480.3
XS Rating Curve= 0 ,0
Exp/Cntr(USF)=0,0
Exp/Cntr=0.3,0.1

Type RM Length L Ch R = 1 ,17707   ,218.7,217.3,213.1
XS GIS Cut Line= 5
2203284.47121777392967.1691902522203354.77974526393324.304551462
2203350.78494256393420.1798162172203362.76935065393500.075870179
2203395.52673278393841.232020597
#Sta/Elev= 30
       0 2583.13    38.7 2573.19    71.4 2567.33    95.8 2558.62   132.5 2543.22
     165 2525.84   193.7 2507.59   218.1 2490.47   250.7 2469.31   263.7 2462.22
   287.6 2451.02   352.7 2414.65   360.8 2408.48   384.9 2385.61   388.9 2383.61
   396.9 2381.97   408.9 2381.33   417.3 2382.31   432.9 2382.96   452.9 2386.41
   485.2 2385.18   517.6 2385.92   593.7 2398.19   606.1 2398.73   610.2 2399.86
   702.6 2439.46   754.8 2466.95     803 2489.17   847.3 2507.35   883.5 2520.89
#Mann= 3 ,-1,0
       0      .1       0   396.9    .045       0   417.3      .1       0
#XS Ineff= 2 , 0
                          458.03         2398.31
Permanent Ineff=
       F       F
Bank Sta=396.9,417.3
XS Rating Curve= 0 ,0
Exp/Cntr(USF)=0,0
Exp/Cntr=0.3,0.1

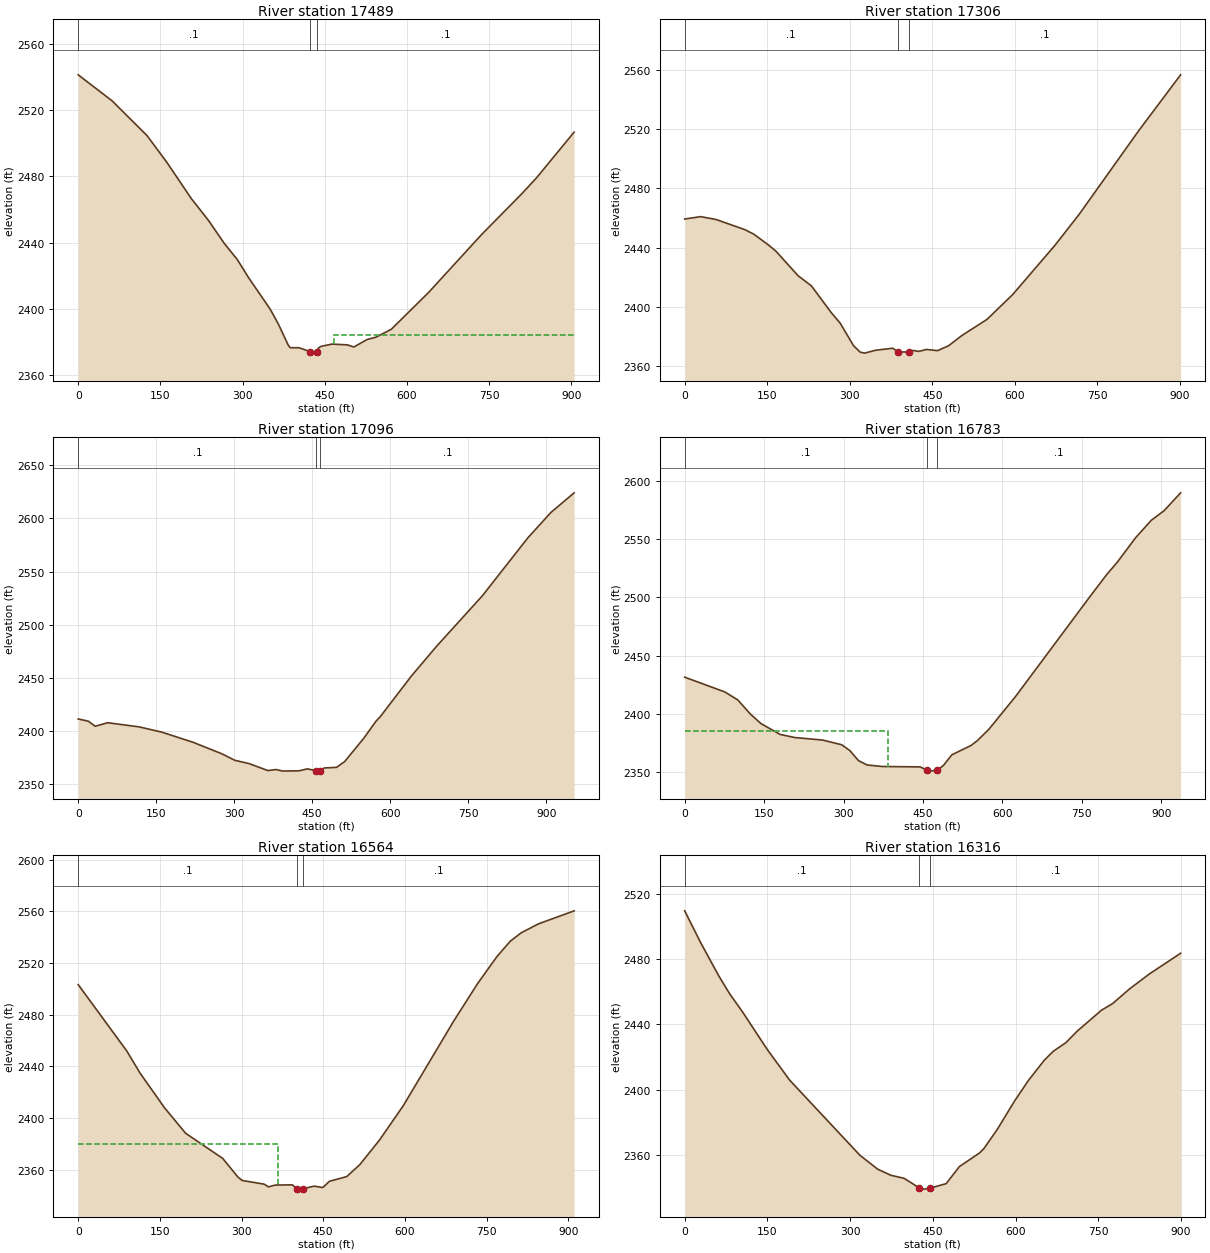
Type RM Length L Ch R = 1 ,17489   ,183.6,183.6,183.3
XS GIS Cut Line= 2
2203108.49769876392987.7391715792203184.59497485393889.770297843
#Sta/Elev= 30
       0 2541.33    61.7 2525.68   125.9 2504.57     162 2488.44   206.2  2466.8
   238.3 2453.27   266.4 2439.73   290.5 2429.85   310.5 2419.21   350.7 2399.84
   365.8 2390.67   382.8 2378.64   386.8 2376.71   402.9 2376.72   423.1 2374.39
     431 2373.45     435 2374.27     439 2376.68     443 2377.49   463.1  2378.9
   491.2 2378.42   503.2 2377.17   527.3 2381.66   543.4 2383.06   571.5 2387.85
   639.7  2410.1     736  2444.9   808.3 2469.13   836.4 2479.16   905.2 2506.79
#Mann= 3 ,-1,0
       0      .1       0   423.1    .045       0     435      .1       0
#XS Ineff= 2 , 0
                          466.93         2384.14
Permanent Ineff=
       F       F
Bank Sta=423.1,435
XS Rating Curve= 0 ,0
Exp/Cntr(USF)=0,0
Exp/Cntr=0.3,0.1

Type RM Length L Ch R = 1 ,17306   ,214.1,210,208.8
XS GIS Cut Line= 2
 2202921.3243489393044.171064482 2203015.8590379393940.275895582
#Sta/Elev= 30
       0 2459.32    29.2 2460.94    57.3 2458.97   109.6 2452.11   125.7 2449.05
   152.7 2441.64   165.9 2437.55   206.1 2420.96   230.3  2414.1   266.5 2395.94
   282.6 2388.87   306.7 2373.72   318.8 2369.31   326.8 2368.62   346.9 2370.57
   378.3 2371.93   387.1 2369.45   407.3 2369.34   415.3 2370.44   425.1 2369.77
   439.4 2371.11   459.5 2370.31   479.7 2373.66   503.8 2380.56   549.3 2391.44
     596 2408.24     673 2441.65     717 2462.62   825.6  2519.4   901.1 2556.85
#Mann= 3 ,-1,0
       0      .1       0   387.1    .045       0   407.3      .1       0
Bank Sta=387.1,407.3
XS Rating Curve= 0 ,0
Exp/Cntr=0.3,0.1

Type RM Length L Ch R = 1 ,17096   ,311.5,313.1,313.1
XS GIS Cut Line= 2
2202776.80308226393080.4847402452202806.47336343394033.913796882
#Sta/Elev= 30
       0 2411.55    19.5 2409.42    32.7  2404.7    56.7    2408   116.8 2404.12
   160.8 2399.16   220.8 2389.65   276.8 2378.73   300.8 2372.76   328.9 2369.58
   364.8 2363.07   380.9 2364.03   392.9  2362.6   424.9 2362.83   440.9 2364.66
     458 2362.83   464.9 2362.53   465.8  2362.8   472.9 2365.48   496.9 2366.08
   512.4 2371.46     549 2393.23     573 2409.55     581 2413.69     641 2451.94
     689 2479.64   777.1 2527.06   864.6 2581.51   909.1 2605.44   953.9 2623.93
#Mann= 3 ,-1,0
       0      .1       0     458    .045       0   465.8      .1       0
Bank Sta=458,465.8
XS Rating Curve= 0 ,0
Exp/Cntr=0.3,0.1

Type RM Length L Ch R = 1 ,16783   ,217.9,218.3,218.6
XS GIS Cut Line= 2
2202512.23275738393057.1325315552202466.48675738393992.633531555
#Sta/Elev= 30
       0 2431.52    75.8 2418.86   100.2 2412.05   124.2 2399.86   144.2  2391.7
   180.3 2382.45   208.3 2379.76   260.4 2377.63   296.4 2373.61   311.6 2368.76
   328.4 2359.97   344.5 2356.29   372.5 2354.98   444.6 2354.62   458.3 2351.81
   464.6    2351   477.4  2351.8   488.6 2355.85   504.6    2365   540.7 2372.95
   552.7 2377.12   574.5 2386.88   624.8 2414.92   767.5 2501.86     797 2519.45
   816.9 2529.97   851.5 2550.96   881.1 2565.91   905.3 2574.14   936.6 2589.49
#Mann= 3 ,-1,0
       0      .1       0   458.3    .045       0   477.4      .1       0
#XS Ineff= 2 , 0
          384.02 2385.45
Permanent Ineff=
       F       F
Bank Sta=458.3,477.4
XS Rating Curve= 0 ,0
Exp/Cntr=0.3,0.1

Type RM Length L Ch R = 1 ,16564   ,248.1,248.3,247.4
XS GIS Cut Line= 3
2202276.18301677 393055.853810152202285.77054325 393539.22493662
2202296.15703026393966.668825317
#Sta/Elev= 30
       0 2503.21    89.3 2451.83   113.3 2434.97   158.2 2408.12   197.3 2388.23
   265.4 2368.77   293.4 2354.34   301.4 2351.67   341.4 2348.86   349.4 2346.77
   362.2 2348.14   393.4  2348.3   401.4 2345.33   401.4 2345.31   405.4    2345
   413.6 2345.45   433.4  2347.3   449.4 2346.25   461.4 2351.06   493.4 2354.72
   517.4 2364.01   553.4 2382.95   597.1 2409.53   689.5 2474.84   733.8 2504.12
   769.5 2525.08   793.5 2536.72   813.5 2543.25   845.5 2550.22     911  2560.3
#Mann= 3 ,-1,0
       0      .1       0   401.4    .045       0   413.6      .1       0
#XS Ineff= 2 , 0
          367.13 2379.56
Permanent Ineff=
       F       F
Bank Sta=401.4,413.6
XS Rating Curve= 0 ,0
Exp/Cntr(USF)=0,0
Exp/Cntr=0.3,0.1

Type RM Length L Ch R = 1 ,16316   ,251.2,253.1,252.3
XS GIS Cut Line= 3
2202033.37940596393043.7715863582202058.93695454393527.861624118
2202104.03851085393939.789171777
#Sta/Elev= 30
       0 2509.74    29.4 2489.94    61.5    2470    81.5 2458.86   105.6 2447.34
   149.6 2424.68   190.4 2405.77   317.8 2359.65   349.9 2351.15   373.9 2347.38
     398  2345.5   425.6 2339.56   433.9 2338.88   445.3 2339.52   474.1 2342.25
   498.2 2352.76   534.4 2361.02   542.4 2363.73   566.6 2375.44   597.8  2392.8
   622.9 2405.43     652 2418.01   668.4 2423.53   691.3 2428.84   711.4 2435.78
   755.7 2448.73   775.8 2452.77   806.2 2461.68   841.8  2470.8   899.2  2483.7
#Mann= 3 ,-1,0
       0      .1       0   425.6    .045       0   445.3      .1       0
Bank Sta=425.6,445.3
XS Rating Curve= 0 ,0
Exp/Cntr(USF)=0,0
Exp/Cntr=0.3,0.1

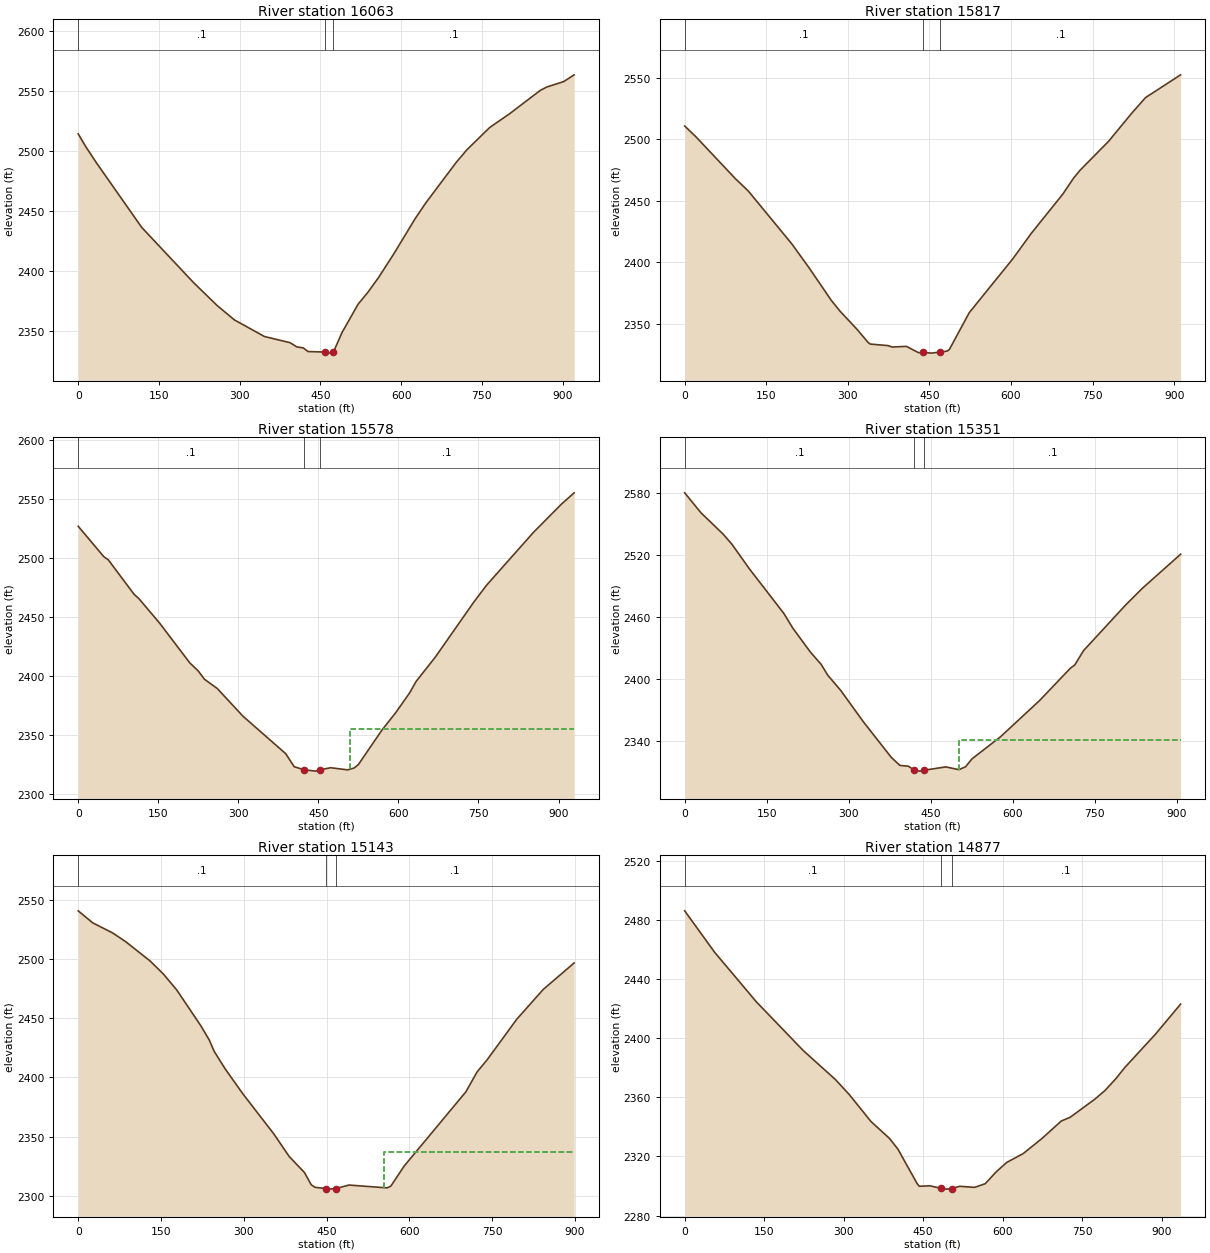
Type RM Length L Ch R = 1 ,16063   ,243.9,246.2,247
XS GIS Cut Line= 2
     2201821.107      393063.071     2201808.438      393984.474
#Sta/Elev= 30
       0 2514.04    14.1 2503.36    34.1 2489.79   118.1 2436.12   214.1 2390.33
   258.1 2371.17   290.1 2359.22   346.1 2345.35   393.7 2340.22   406.1 2336.73
   418.1 2335.88   427.1 2332.83   458.2 2332.44   466.2 2331.53   474.2 2332.39
   490.2 2348.66   519.9 2372.15   538.2 2382.15   558.2 2394.54   586.2 2414.01
   625.8 2443.27   646.1 2456.75   702.2  2490.2   722.2 2500.78   764.6 2519.35
   802.2 2530.99   858.2 2550.11   870.2 2552.95   902.2 2557.58   921.5 2563.18
#Mann= 3 ,-1,0
       0      .1       0   458.2    .045       0   474.2      .1       0
Bank Sta=458.2,474.2
XS Rating Curve= 0 ,0
Exp/Cntr=0.3,0.1

Type RM Length L Ch R = 1 ,15817   ,241.1,238.3,233.5
XS GIS Cut Line= 4
2201606.96851945393032.2839185552201584.69614596393423.906485719
2201562.42377247393564.9648511432201560.56774135393941.739169315
#Sta/Elev= 30
       0 2510.93    20.9 2502.03      93 2468.12   117.1  2457.9   197.2 2414.75
   229.3 2395.03   269.3 2369.02   285.4 2360.16   316.6  2345.4   337.4 2334.47
   341.4 2333.23   373.5 2332.01   381.5 2330.84   407.8 2331.36     430 2326.22
   438.1 2326.48   453.3 2325.86   470.1 2326.71   482.6 2327.53   486.7 2328.83
   523.1 2358.77   603.3 2402.71   637.5 2423.59   695.3 2455.47   715.3 2468.63
   727.3 2475.06   779.3 2498.41   822.4 2521.58   847.3 2534.07   911.8 2552.62
#Mann= 3 ,-1,0
       0      .1       0   438.1    .045       0   470.1      .1       0
Bank Sta=438.1,470.1
XS Rating Curve= 0 ,0
Exp/Cntr(USF)=0,0
Exp/Cntr=0.3,0.1

Type RM Length L Ch R = 1 ,15578   ,227.1,227.4,227.8
XS GIS Cut Line= 2
2201333.49973271393024.8276833672201377.57438589393953.130910506
#Sta/Elev= 30
       0 2526.84    48.4 2500.86    56.4 2498.41   104.5 2469.25   113.8 2465.45
   152.5 2444.74   209.3 2410.87   224.6 2404.33   236.6 2397.09   260.6 2389.25
   308.7 2365.77   388.8 2333.99   404.8 2322.93   423.4  2320.3   444.9 2319.18
   452.9 2320.23   472.9 2322.07   504.9 2320.25   516.9 2321.83   524.9 2324.69
   568.7 2353.71   595.5 2369.11   621.1 2385.61   633.1 2395.22   669.1 2415.86
   740.7  2462.2   765.2 2476.86   853.3  2521.8   905.6 2545.66   929.3 2555.22
#Mann= 3 ,-1,0
       0      .1       0   423.4    .045       0   452.9      .1       0
#XS Ineff= 2 , 0
                          509.98          2354.7
Permanent Ineff=
       F       F
Bank Sta=423.4,452.9
XS Rating Curve= 0 ,0
Exp/Cntr=0.3,0.1

Type RM Length L Ch R = 1 ,15351   ,206.9,208,206.7
XS GIS Cut Line= 2
 2201131.8339652393055.5013115892201129.29758519393962.814828656
#Sta/Elev= 30
       0 2580.35    29.7 2561.11    69.7 2540.75    86.3 2530.71   118.3 2506.89
   181.7 2463.47   197.7 2449.57   229.7 2426.47   249.7 2414.37   261.7 2403.96
   285.7 2389.01   326.9 2358.85   377.7 2324.59   393.7 2316.63   409.7  2315.8
   420.2 2311.86   429.7  2311.1   437.7 2311.95   477.7  2315.2   501.7 2312.51
   513.7 2315.26   525.7    2323   577.7  2344.3   649.7 2379.61   705.7 2410.73
   713.7 2413.84   729.7 2427.69   807.1 2472.06   837.7 2488.18   907.3 2520.96
#Mann= 3 ,-1,0
       0      .1       0   420.2    .045       0   437.7      .1       0
#XS Ineff= 2 , 0
                           502.3         2341.44
Permanent Ineff=
       F       F
Bank Sta=420.2,437.7
XS Rating Curve= 0 ,0
Exp/Cntr=0.3,0.1

Type RM Length L Ch R = 1 ,15143   ,266,265.5,264.4
XS GIS Cut Line= 2
2200944.36540818393050.8442297952200916.52494132393949.163293811
#Sta/Elev= 30
       0 2540.87    26.3 2530.72    62.4 2522.17    86.4 2514.67   130.4 2498.44
   154.4 2487.43   178.4 2474.07   222.4  2443.6   237.6 2431.58   246.5 2421.99
   266.5 2407.14   298.5 2386.09   354.5 2352.27   382.5 2333.09     410 2319.63
   422.5 2309.14   429.4 2307.09   448.8 2306.08   454.6 2305.57   466.6 2306.01
   490.6 2309.02   559.8 2306.62   566.6 2308.14   590.6    2325   702.7 2387.93
   722.7 2404.53   741.5 2415.18   794.7 2449.16   842.7 2474.37   898.8 2496.82
#Mann= 3 ,-1,0
       0      .1       0   448.8    .045       0   466.6      .1       0
#XS Ineff= 2 , 0
                          554.53         2337.22
Permanent Ineff=
       F       F
Bank Sta=448.8,466.6
XS Rating Curve= 0 ,0
Exp/Cntr(USF)=0,0
Exp/Cntr=0.3,0.1

Type RM Length L Ch R = 1 ,14877   ,222.6,231.3,244.2
XS GIS Cut Line= 4
2200753.63941325393037.4129904652200680.34025775393436.893387941
2200696.83256773393625.638713355 2200614.3710178393955.484913106
#Sta/Elev= 30
       0 2486.34    56.7 2458.19   135.1 2424.76   223.4 2391.83   284.4 2372.07
   310.3    2362   351.5 2343.66   386.4  2332.2   402.4  2324.9   438.6 2301.57
   442.6 2299.81   462.6 2300.11   483.8 2298.41   494.8 2297.87   503.4 2298.28
   518.9 2299.78     547 2299.07     567 2301.54   587.1 2309.36   607.5 2315.93
   638.7 2321.96   673.5    2332   710.6 2344.03   727.1 2346.48   773.9 2358.83
     793 2364.67   813.7 2372.77     830 2380.11   887.9 2402.71   935.6 2423.17
#Mann= 3 ,-1,0
       0      .1       0   483.8    .045       0   503.4      .1       0
Bank Sta=483.8,503.4
XS Rating Curve= 0 ,0
Exp/Cntr(USF)=0,0
Exp/Cntr=0.3,0.1

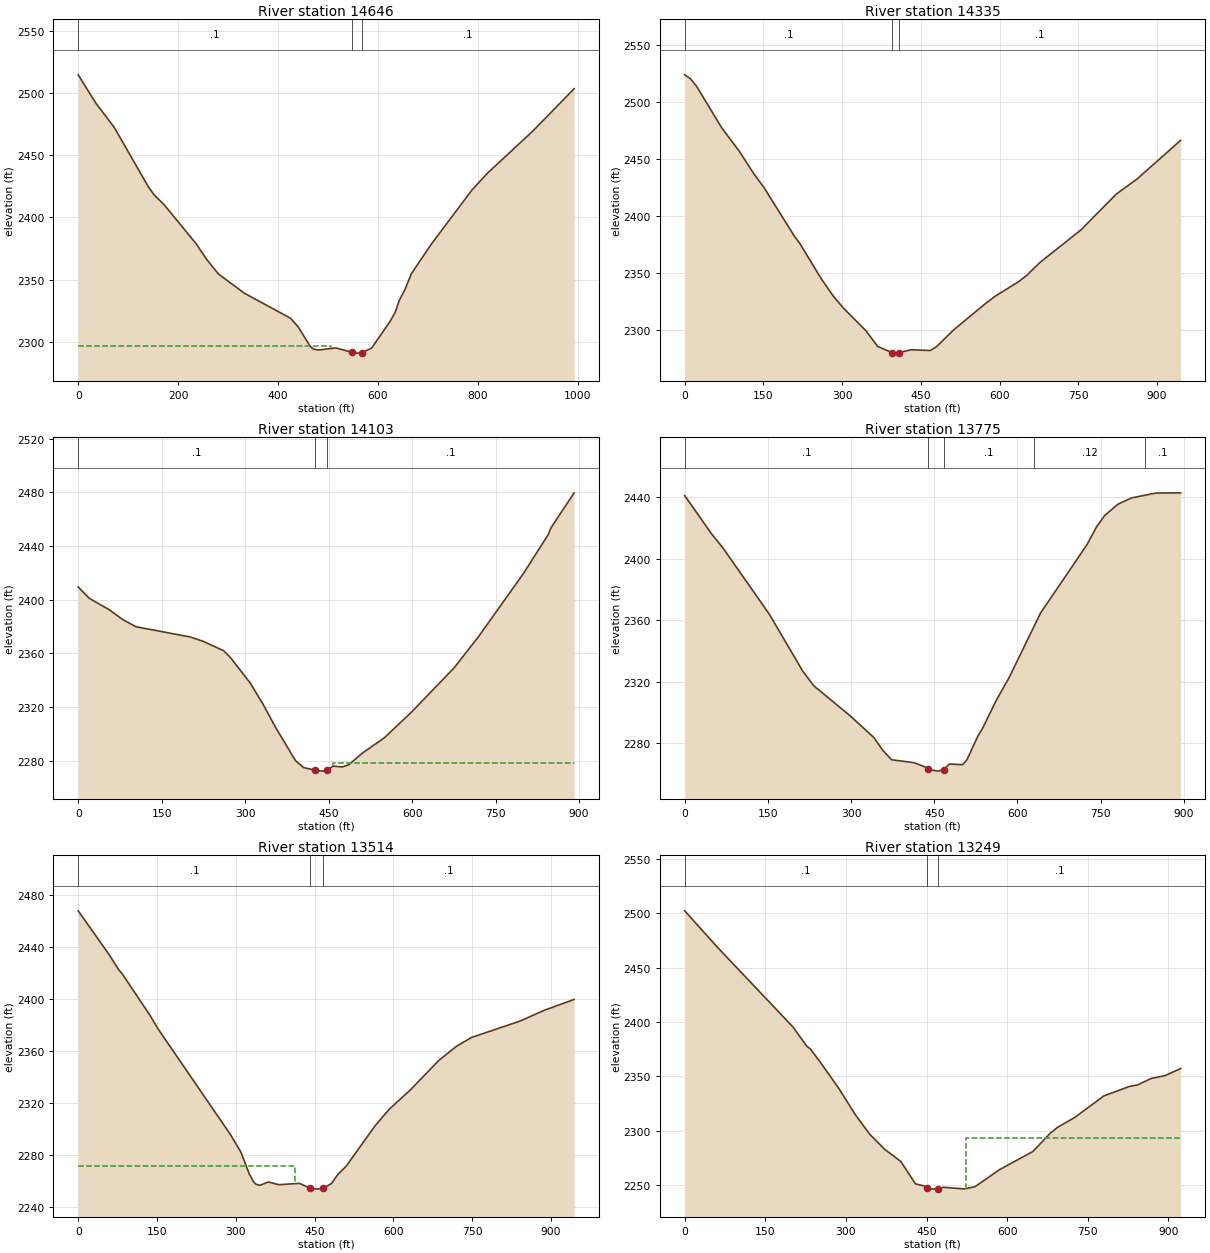
Type RM Length L Ch R = 1 ,14646   ,317.8,311.2,305.8
XS GIS Cut Line= 4
 2200575.0152145392965.466798091 2200543.4626854393390.497925487
2200422.82066234393544.5485087792200374.56385311393912.042671331
#Sta/Elev= 30
       0 2514.92    35.8 2491.81    71.9 2472.71   140.5 2424.66   151.7 2418.34
   172.2 2410.18   236.4 2378.69   256.4 2366.59   280.5 2354.54   332.6 2338.99
   424.9 2318.86   439.8 2312.13   464.6 2296.11   470.3 2294.04   480.4 2293.25
     516 2294.94   548.3 2291.35   558.7 2290.75   567.8 2291.12   587.2 2294.79
   624.8 2316.74   634.6 2323.89   642.6 2333.34   653.3 2341.46   666.9 2354.81
   707.2 2378.83   787.9 2422.08   819.2 2435.77   910.1 2469.75   992.5 2503.76
#Mann= 3 ,-1,0
       0      .1       0   548.3    .045       0   567.8      .1       0
#XS Ineff= 2 , 0
          506.49 2296.86
Permanent Ineff=
       F       F
Bank Sta=548.3,567.8
XS Rating Curve= 0 ,0
Exp/Cntr(USF)=0,0
Exp/Cntr=0.3,0.1

Type RM Length L Ch R = 1 ,14335   ,230.8,231.6,229.4
XS GIS Cut Line= 3
2200268.77007904392878.2333352632200235.36151881393375.649676495
2200205.66502083393821.097146255
#Sta/Elev= 30
       0  2524.1    11.1 2520.68      23 2513.84    71.1 2477.25   104.8 2456.64
   131.2 2437.71   151.3 2425.08   209.9 2381.98   219.4  2376.2   259.5 2345.76
   283.6  2329.7   303.6 2318.95   345.2 2299.71   367.7 2285.86   395.8 2280.26
   403.9 2279.96   407.9 2280.38   431.9 2282.95     468 2282.24     480 2285.65
   512.1 2300.17   572.2  2323.1   592.3  2330.1   636.4 2342.66   652.4  2348.4
   676.5 2359.32   754.8 2387.92   822.4 2419.48   861.9 2432.67     945 2466.62
#Mann= 3 ,-1,0
       0      .1       0   395.8    .045       0   407.9      .1       0
Bank Sta=395.8,407.9
XS Rating Curve= 0 ,0
Exp/Cntr(USF)=0,0
Exp/Cntr=0.3,0.1

Type RM Length L Ch R = 1 ,14103   ,324.5,328.1,329.9
XS GIS Cut Line= 3
2199977.37319258392909.7858643712200036.76618854393457.315045951
2199994.07747269393795.112710519
#Sta/Elev= 30
       0 2409.45    20.1 2400.95    55.7 2392.51    79.9 2385.21     104  2379.8
   201.6 2372.15   224.7 2368.88   260.9 2362.02     273 2357.13   309.2 2337.75
   332.3 2321.93   353.5 2305.57   390.4 2279.96   404.9  2274.8   425.9 2272.72
   438.4  2272.1   447.5 2272.71   458.1 2275.86   474.2  2275.2   486.2 2276.86
   510.2 2285.39   550.1 2296.99     599 2316.15   675.6 2349.21   719.4 2372.43
   800.6 2419.83   844.7 2448.58     849 2453.09     853 2455.81   891.2  2479.7
#Mann= 3 ,-1,0
       0      .1       0   425.9    .045       0   447.5      .1       0
#XS Ineff= 2 , 0
                          458.42         2278.38
Permanent Ineff=
       F       F
Bank Sta=425.9,447.5
XS Rating Curve= 0 ,0
Exp/Cntr(USF)=0,0
Exp/Cntr=0.3,0.1

Type RM Length L Ch R = 1 ,13775   ,262.9,261.2,257.9
XS GIS Cut Line= 2
2199723.06717756392892.3778132562199682.20620436393785.661418818
#Sta/Elev= 30
       0 2441.06    48.9 2415.96    68.9 2407.07     153 2363.72     213 2326.87
     233 2317.35   298.4 2297.87   341.2 2283.76   357.2  2275.5   373.2 2269.33
   413.2 2267.44   433.3 2264.76   438.4 2263.02   457.3 2261.95   466.8 2262.86
   477.3 2266.58     501 2266.13     509 2269.31   528.1 2284.33   537.4 2289.95
   561.4 2307.68   585.3 2322.96   641.5 2364.62   725.6 2409.25   742.5 2420.62
   757.6 2428.23   781.6  2435.5   805.6 2439.51   849.6 2442.67   894.2 2442.82
#Mann= 5 ,-1,0
       0      .1       0   438.4    .045       0   466.8      .1       0
     630     .12       0     830      .1       0
Bank Sta=438.4,466.8
XS Rating Curve= 0 ,0
Exp/Cntr=0.3,0.1

Type RM Length L Ch R = 1 ,13514   ,273.2,265.1,254.7
XS GIS Cut Line= 3
2199397.56250605392877.4740933722199450.26035336393384.929832115
2199577.83478213393799.491062248
#Sta/Elev= 30
       0 2467.98    59.6 2433.83    76.1 2423.17    84.2 2419.22   136.4 2387.65
   152.5 2376.75   289.3 2295.97   309.4 2282.45   325.4 2265.61   333.6 2259.49
   337.5 2257.66   345.6 2256.56   361.6 2259.21   381.7 2257.12   421.1  2258.1
   442.1 2254.39   454.1 2253.69   466.2 2254.36   482.3 2258.11   494.3 2265.07
   510.2 2271.46   564.9 2302.39   591.9 2315.18   631.8 2329.97   686.2 2352.74
   719.7  2363.6   748.7 2370.48   841.1 2383.12   887.1 2391.41   943.9 2399.75
#Mann= 3 ,-1,0
       0      .1       0   442.1    .045       0   466.2      .1       0
#XS Ineff= 2 , 0
          412.96 2271.56
Permanent Ineff=
       F       F
Bank Sta=442.1,466.2
XS Rating Curve= 0 ,0
Exp/Cntr=0.3,0.1

Type RM Length L Ch R = 1 ,13249   ,179,178.8,179.9
XS GIS Cut Line= 2
2198931.67529658 393086.834135272199502.05029658 393811.96813527
#Sta/Elev= 30
       0 2502.26    61.8  2468.3   201.5  2395.4   226.9 2377.88   233.7 2375.24
   252.4 2362.95   286.9 2338.84   317.8 2314.46   344.8 2296.48   372.3 2282.82
   401.9 2271.83   429.3 2251.17   445.7 2249.14451.67862246.878   466.3 2246.27
   471.2 2246.61   480.6 2247.97   520.5 2246.47   540.4 2248.59     586  2264.3
   647.8 2280.88   679.8 2297.54   694.2 2303.31   725.6 2312.22   779.7 2331.96
   827.4 2340.74   842.7 2342.15   868.1 2348.14   893.6 2350.66   922.6 2357.19
#Mann= 3 ,-1,0
       0      .1       0451.6786    .045       0   471.2      .1       0
#XS Ineff= 2 , 0
                          523.81         2293.29
Permanent Ineff=
       F       F
Bank Sta=451.6786,471.2
XS Rating Curve= 0 ,0
Exp/Cntr=0.3,0.1