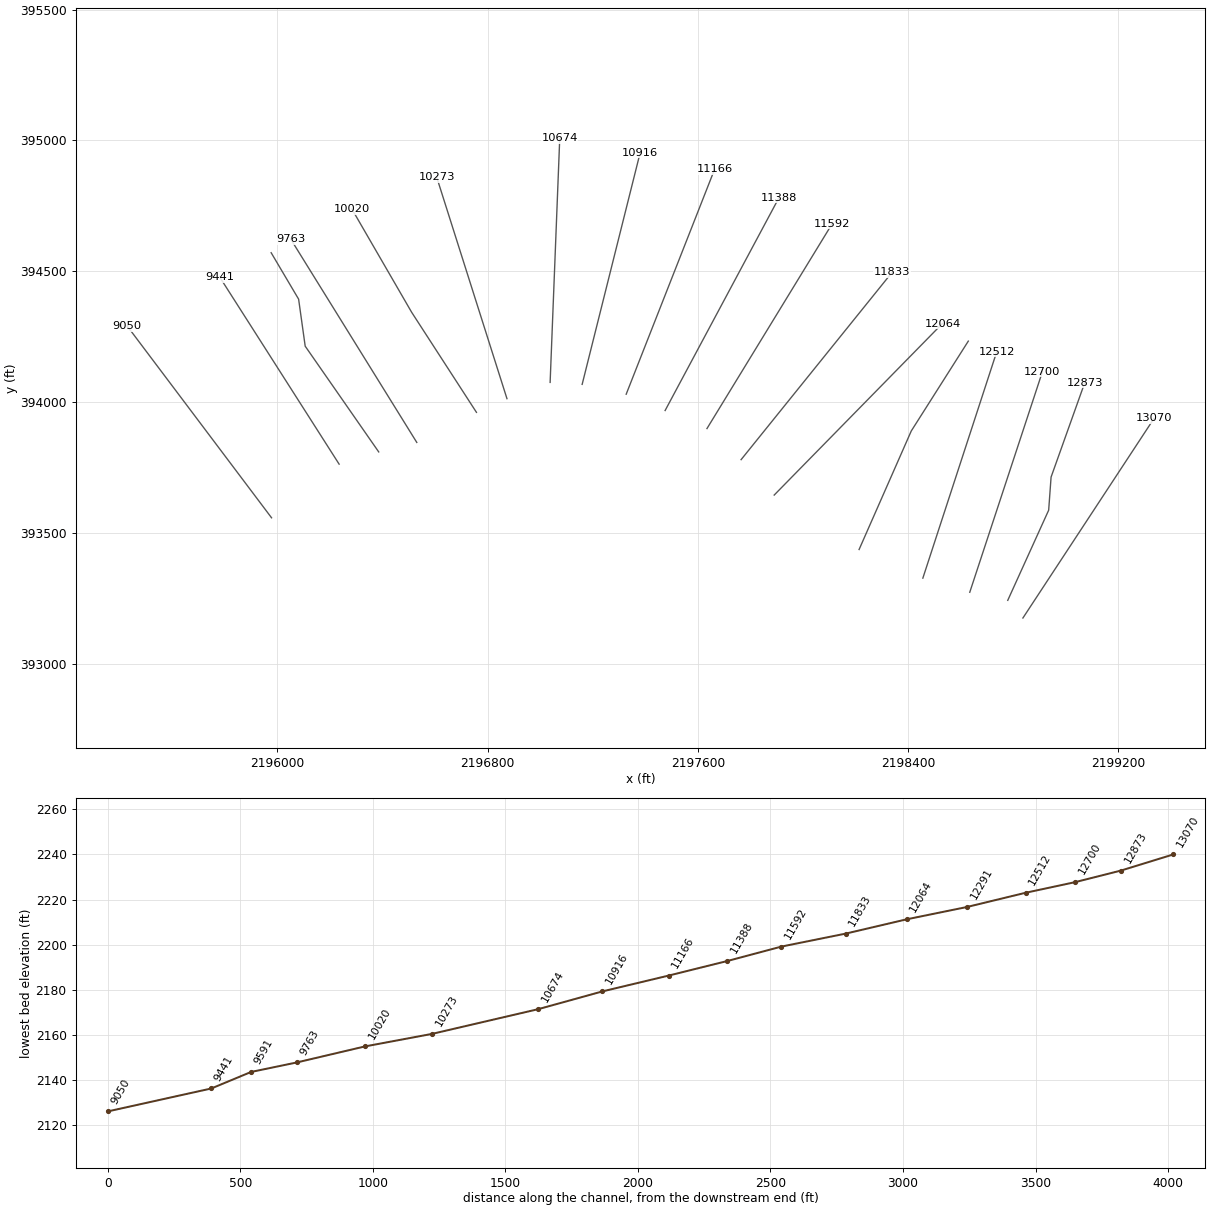
HEC-RAS study OLDHMRN.prj: OLDHMRN

--- OLDHMRN.g01 (geometry) --- (continued)

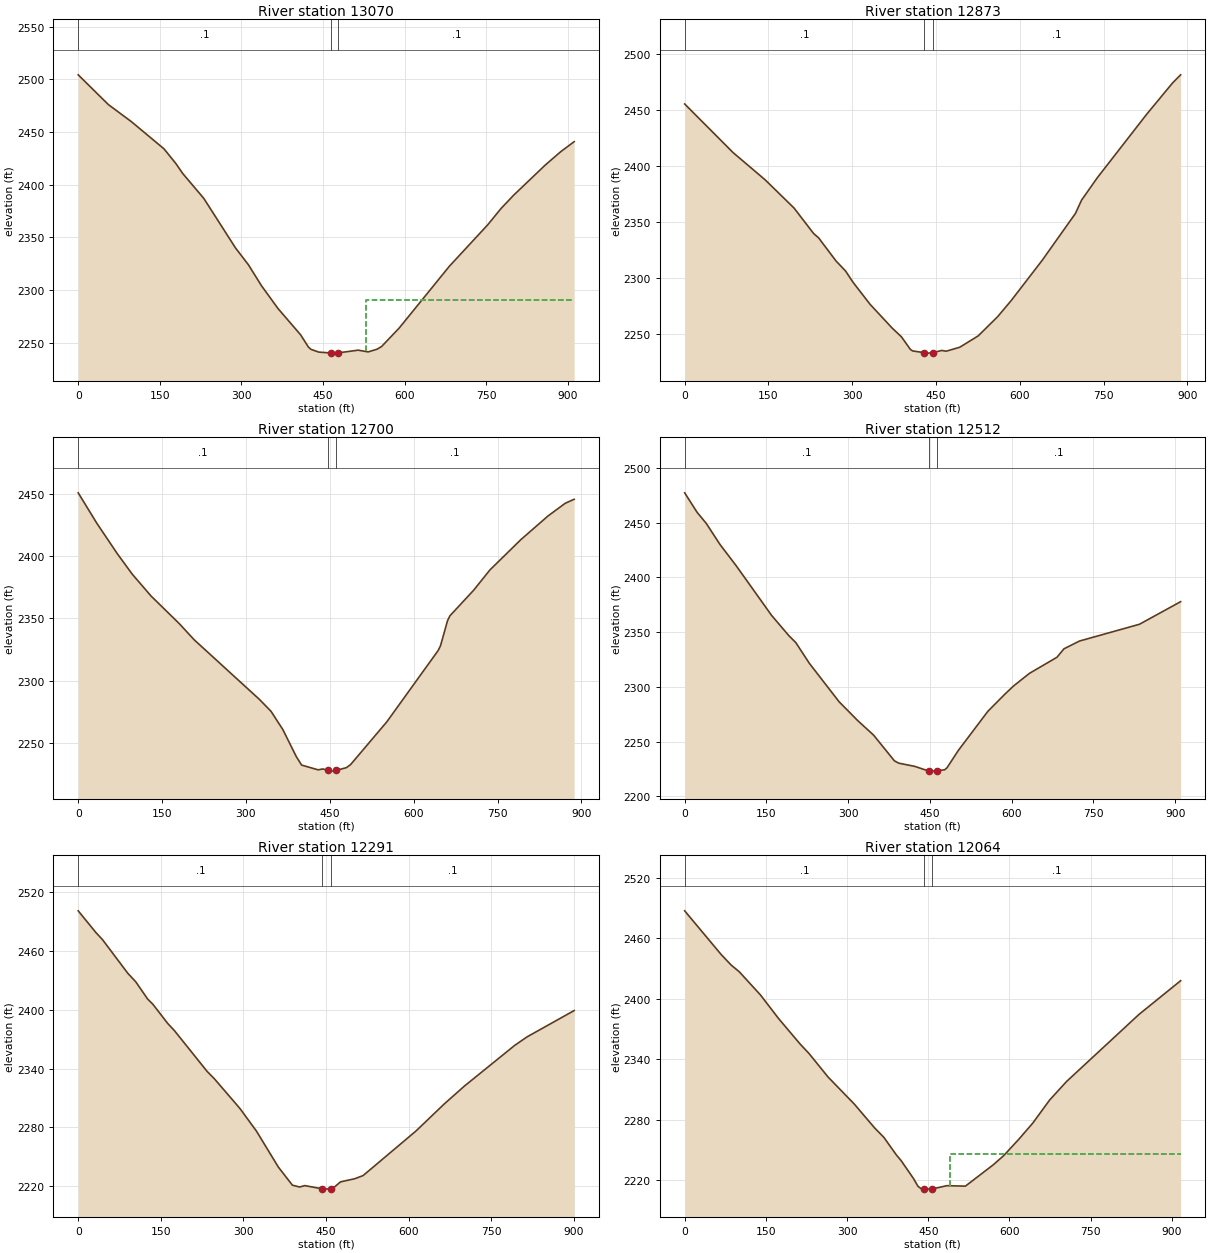
Type RM Length L Ch R = 1 ,13070   ,189.4,197.7,202.1
XS GIS Cut Line= 2
2198837.77008244393175.198315103 2199337.0424548393938.027107067
#Sta/Elev= 30
       0 2504.31    55.5 2476.03      98 2459.74   157.8 2433.96   179.7 2419.94
   192.2 2410.54   230.8 2387.01   289.2 2339.87   313.1 2323.77     337 2303.92
   367.2  2282.4   408.7 2257.47   423.1 2245.82   427.9 2243.56   442.2 2240.97
   463.92240.131   466.1 2239.98   478.32240.249   514.6 2242.79     533 2241.15
   549.3 2243.67   557.9 2246.35   590.4 2264.01   682.2 2322.43   752.9 2361.91
   777.5 2377.47   800.5 2389.98   858.4 2418.53   887.3 2431.44   911.7 2440.82
#Mann= 3 ,-1,0
       0      .1       0   463.9    .045       0   478.3      .1       0
#XS Ineff= 2 , 0
                          528.42         2290.72
Permanent Ineff=
       F       F
Bank Sta=463.9,478.3
XS Rating Curve= 0 ,0
Exp/Cntr(USF)=0,0
Exp/Cntr=0.3,0.1

Type RM Length L Ch R = 1 ,12873   ,176.6,172.3,170.4
XS GIS Cut Line= 4
 2198780.0596514393242.6506258662198935.82035684393587.156656717
2198944.98275128393713.597699955 2199073.2562734394074.596040794
#Sta/Elev= 30
       0 2455.67    86.6 2412.22   144.1 2387.83   195.9 2362.55     231 2339.73
   239.8 2335.94     271 2315.25   288.1 2306.27   301.3  2296.3     332 2276.48
   371.5 2255.25   388.1 2247.43   404.2 2236.13   408.2 2234.81   428.9 2233.23
   436.3 2232.83   444.3 2233.26   460.3 2235.21   468.3 2234.56   492.5 2238.08
   525.6 2248.27   560.3 2265.39   585.1 2280.12   640.3 2315.95   699.7 2357.77
   710.6 2369.61   738.8 2389.67     827 2446.32   873.7 2474.52     888 2481.73
#Mann= 3 ,-1,0
       0      .1       0   428.9    .045       0   444.3      .1       0
Bank Sta=428.9,444.3
XS Rating Curve= 0 ,0
Exp/Cntr(USF)=0,0
Exp/Cntr=0.3,0.1

Type RM Length L Ch R = 1 ,12700   ,187.8,187.8,187.9
XS GIS Cut Line= 2
2198635.46268993393273.567964675 2198912.0113274 394116.20609497
#Sta/Elev= 30
       0  2450.6    33.3 2426.24      70  2401.8    96.4 2385.59   130.2    2368
   180.6 2345.91   207.5 2332.86   323.8 2285.28   344.8 2275.63   365.9 2261.04
   390.1 2239.29   399.5 2232.58     429 2228.75   437.4 2229.46   446.12228.446
   454.3 2227.72     4612228.262   479.5 2230.49   487.1 2232.96   551.8 2267.14
   643.7 2324.31   647.9 2328.15   660.5 2348.25   664.8 2352.14   707.1 2372.57
   736.3 2388.85   791.1 2412.91   840.2 2432.08     871 2442.24   886.9 2445.44
#Mann= 3 ,-1,0
       0      .1       0   446.1    .045       0     461      .1       0
Bank Sta=446.1,461
XS Rating Curve= 0 ,0
Exp/Cntr(USF)=0,0
Exp/Cntr=0.3,0.1

Type RM Length L Ch R = 1 ,12512   ,222.5,221,220.1
XS GIS Cut Line= 2
2198456.87571782393327.5457888752198738.25571782394192.950788875
#Sta/Elev= 30
       0  2477.2    22.7 2459.49    39.6 2449.28    64.8 2430.03    94.3 2410.76
   159.4 2365.31     191 2346.83   203.9 2340.41   228.8 2321.45   283.2 2286.45
   317.2  2269.3   346.7 2255.86   384.8 2232.41   392.9 2230.26   422.3 2227.32
   447.52223.112     456 2222.99   462.52223.255   476.9  2224.2   481.2 2225.95
   502.2 2241.94   556.2 2277.56   587.9 2293.45   603.2 2300.67   632.6 2312.29
   683.2 2327.03   695.9 2334.69   724.4 2341.81   834.5 2357.15     910 2377.76
#Mann= 3 ,-1,0
       0      .1       0   447.5    .045       0   462.5      .1       0
Bank Sta=447.5,462.5
XS Rating Curve= 0 ,0
Exp/Cntr=0.3,0.1

Type RM Length L Ch R = 1 ,12291   ,232.7,227.3,223.8
XS GIS Cut Line= 3
2198214.14362478393436.8987035872198412.73895505393889.770297843
2198629.89459655394233.136055783
#Sta/Elev= 30
       0 2501.19    32.1 2479.02      44 2471.84    89.9 2437.49   104.7 2428.52
   126.2 2410.97   135.7 2405.63   162.7 2385.98   174.4 2378.98   234.1 2337.09
   247.7 2329.27   293.9 2299.04   323.8 2275.96   363.6 2239.19     389 2220.77
   402.1 2218.87   411.6  2220.3   443.72216.945   445.8  2216.7   458.72217.083
   463.3 2217.81   476.4 2224.12   502.4 2227.34   517.5 2230.57   613.2 2275.97
   664.7 2303.69     702 2322.29   792.8 2363.63   815.2 2372.31   900.8 2399.24
#Mann= 3 ,-1,0
       0      .1       0   443.7    .045       0   458.7      .1       0
Bank Sta=443.7,458.7
XS Rating Curve= 0 ,0
Exp/Cntr(USF)=0,0
Exp/Cntr=0.3,0.1

Type RM Length L Ch R = 1 ,12064   ,229.7,230.6,233.1
XS GIS Cut Line= 2
     2197890.976      393644.957     2198531.245      394300.337
#Sta/Elev= 30
       0 2487.22    67.4 2443.91    85.9 2433.42     101 2426.73   140.1 2403.74
   173.7 2380.27   213.5 2354.98   229.6 2345.82     265 2322.36   313.5 2295.52
   350.9 2271.95   368.1 2262.52   390.9 2245.27   399.8 2239.58   422.5 2221.94
     431 2214.06   436.6 2211.82441.91742211.485   447.7 2211.25456.91132211.458
   484.7 2214.68   518.6  2214.2   569.6 2235.17   589.4 2244.49   617.6 2260.88
   643.1 2276.73   674.2 2299.58   705.3 2317.88   839.1 2384.41   916.2 2417.91
#Mann= 3 ,-1,0
       0      .1       0441.9174    .045       0456.9113      .1       0
#XS Ineff= 2 , 0
                          490.02         2246.32
Permanent Ineff=
       F       F
Bank Sta=441.9174,456.9113
XS Rating Curve= 0 ,0
Exp/Cntr=0.3,0.1

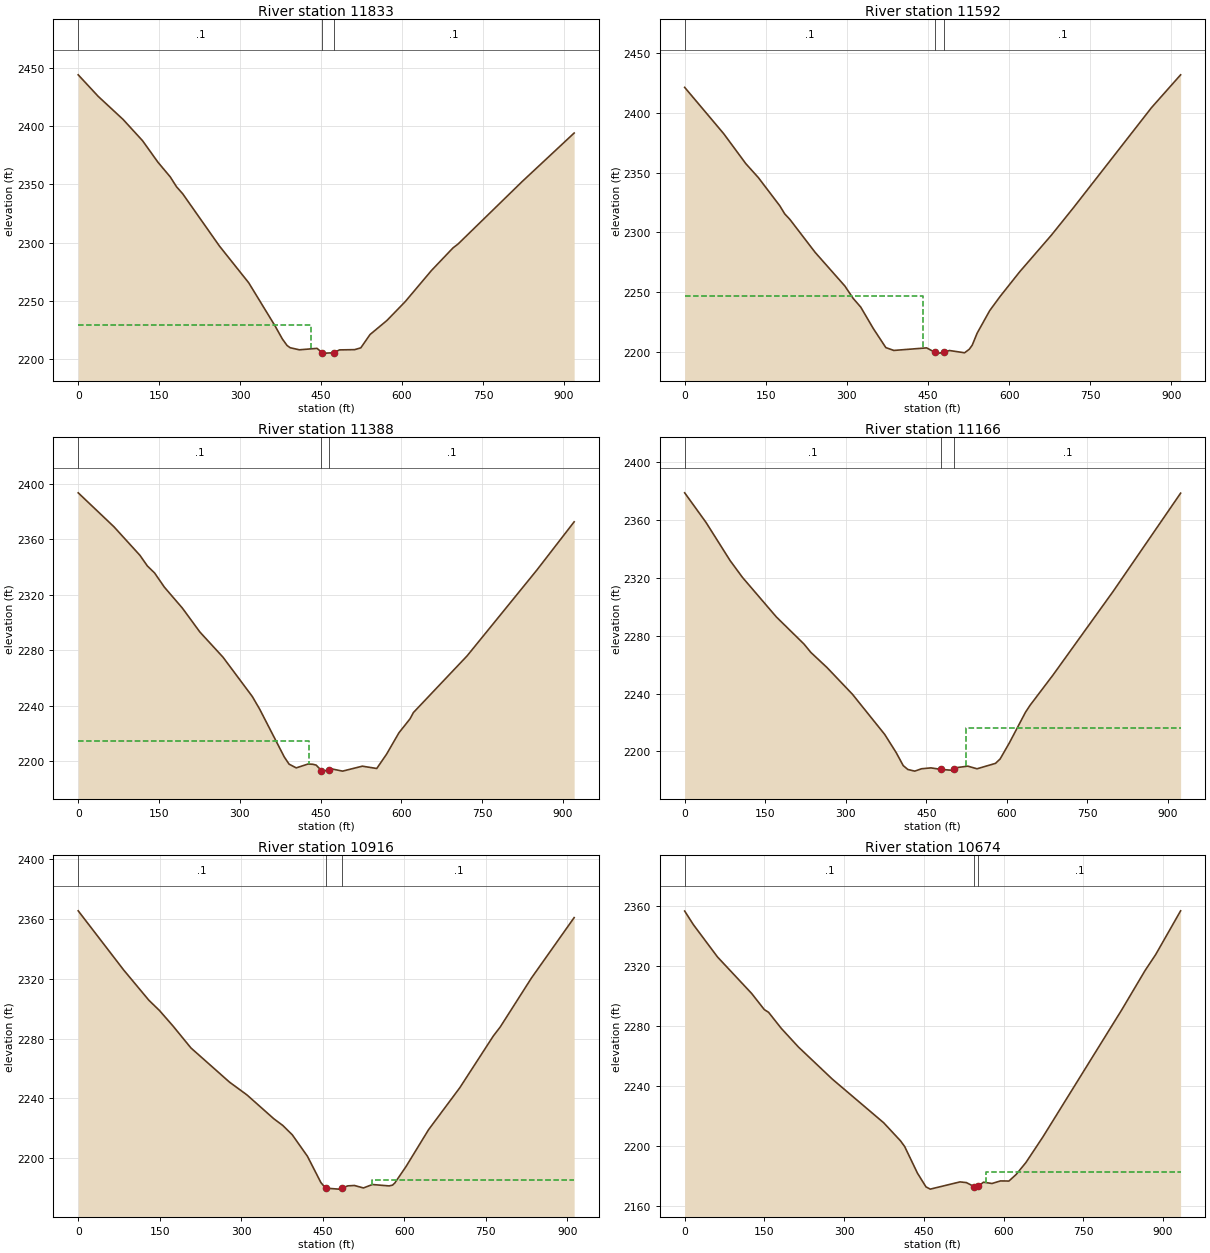
Type RM Length L Ch R = 1 ,11833   ,239.9,242,243.1
XS GIS Cut Line= 2
2197764.98409277393780.2644615272198340.35374121 394496.69247539
#Sta/Elev= 30
       0 2444.13    37.1 2425.59    83.3 2405.71   119.2  2387.5     148 2368.86
   170.5 2356.42   182.2  2347.9   193.6 2341.88   261.8 2296.89   315.9 2265.38
   364.3 2228.63   378.5  2216.9     387 2211.47   392.7 2209.56   409.8 2207.76
   442.4 2209.01   452.5 2205.18   458.2 2204.91   473.2 2205.22   484.2 2207.69
   512.2  2207.9   523.6 2209.46   540.7 2220.89     572 2232.98   605.6 2249.02
   654.5 2275.92   694.3 2295.29     704 2298.78   822.3 2352.27   918.9  2394.1
#Mann= 3 ,-1,0
       0      .1       0   452.5    .045       0   473.2      .1       0
#XS Ineff= 2 , 0
          431.64 2229.01
Permanent Ineff=
       F       F
Bank Sta=452.5,473.2
XS Rating Curve= 0 ,0
Exp/Cntr(USF)=0,0
Exp/Cntr=0.3,0.1

Type RM Length L Ch R = 1 ,11592   ,202.4,203.9,204.7
XS GIS Cut Line= 2
2197635.06191409393899.0504534632198112.06191296 394682.29558779
#Sta/Elev= 30
       0 2421.11    72.2 2382.42     113 2357.44   136.3 2345.73   175.8 2322.26
   185.1 2315.42   194.5 2310.88   241.3  2283.3   296.3 2255.19   311.6 2244.87
   325.5 2237.66   348.7  2219.8     372  2203.8   386.7 2201.43   447.4 2203.56
   462.3 2199.97   470.8 2199.18   480.2 2199.93   489.6 2201.37   517.6 2199.47
   526.3 2202.41   531.7  2205.8   540.8 2215.81   564.1  2234.7   583.2 2246.46
   619.4 2267.06   677.7 2297.47   719.1 2320.71   863.4 2404.26   917.1 2431.59
#Mann= 3 ,-1,0
       0      .1       0   462.3    .045       0   480.2      .1       0
#XS Ineff= 2 , 0
          440.86 2246.69
Permanent Ineff=
       F       F
Bank Sta=462.3,480.2
XS Rating Curve= 0 ,0
Exp/Cntr(USF)=0,0
Exp/Cntr=0.3,0.1

Type RM Length L Ch R = 1 ,11388   ,219.7,222.1,223.9
XS GIS Cut Line= 2
2197475.74913659393967.9712138362197908.82113659394780.574213836
#Sta/Elev= 30
       0 2393.42    66.3 2368.98   114.7 2348.33   128.3 2340.75   141.9 2335.61
     160 2325.41   193.4 2310.33   225.9 2293.09   268.8 2274.95   323.2 2246.62
   336.8 2237.56   382.6 2203.01   391.5 2197.84   404.8 2195.15     427 2197.96
   435.9 2197.72   441.8 2197.13   451.7 2193.15   465.4 2193.27   472.8 2194.23
   490.9  2192.8   527.5 2196.37   554.3  2194.7   572.5    2205   595.5 2220.44
   616.2 2230.57   622.3    2235   722.1 2275.91   851.4 2337.66   920.8 2372.52
#Mann= 3 ,-1,0
       0      .1       0   451.7    .045       0   465.4      .1       0
#XS Ineff= 2 , 0
          427.88 2214.86
Permanent Ineff=
       F       F
Bank Sta=451.7,465.4
XS Rating Curve= 0 ,0
Exp/Cntr=0.3,0.1

Type RM Length L Ch R = 1 ,11166   ,246.4,249.4,249.7
XS GIS Cut Line= 2
2197327.55121853394030.3213992532197664.28607947394890.165159303
#Sta/Elev= 30
       0 2378.79    39.7 2358.35    84.7 2331.88   107.6 2320.31   170.6    2293
   222.2  2274.2     235  2268.4   265.1 2257.94   312.4 2239.48   372.5 2211.69
     394 2199.03   406.9 2190.16   415.5 2187.47   428.4 2186.33   441.2 2187.98
   458.4 2188.57   478.1  2187.5   497.1 2186.93   501.4 2187.71   505.7 2188.72
   527.2 2189.77   544.3 2187.95   578.7 2191.69   587.3 2194.72   604.5 2205.84
   634.6 2227.07   643.1 2231.87   686.1 2252.94   797.8 2310.66   923.4 2378.55
#Mann= 3 ,-1,0
       0      .1       0   478.1    .045       0   501.4      .1       0
#XS Ineff= 2 , 0
                          523.81         2215.84
Permanent Ineff=
       F       F
Bank Sta=478.1,501.4
XS Rating Curve= 0 ,0
Exp/Cntr=0.3,0.1

Type RM Length L Ch R = 1 ,10916   ,242.9,242.5,240.8
XS GIS Cut Line= 2
2197159.91794635394067.949285747 2197380.7856501394953.276131894
#Sta/Elev= 30
       0 2365.54    83.7 2325.93   129.9 2305.77   149.7 2298.78   174.4 2288.48
   207.4  2273.8   278.4 2250.92   310.5 2242.37   359.9 2226.42   376.4 2221.95
   393.9 2215.68   421.8 2201.31   446.5 2183.75   455.32179.978   479.5 2179.34
   486.2 2180.17   496.1 2181.53   508.3 2181.77   524.8 2180.13   541.3 2182.42
     572 2181.49   578.4 2182.04   582.6 2183.48   603.2 2194.47   644.6 2219.09
   702.1 2247.18   763.9 2281.87   776.3 2287.72     834 2320.62   912.5    2361
#Mann= 3 ,-1,0
       0      .1       0   455.3    .045       0   486.2      .1       0
#XS Ineff= 2 , 0
                          539.78         2185.63
Permanent Ineff=
       F       F
Bank Sta=455.3,486.2
XS Rating Curve= 0 ,0
Exp/Cntr(USF)=0,0
Exp/Cntr=0.3,0.1

Type RM Length L Ch R = 1 ,10674   ,397.6,400.9,400.3
XS GIS Cut Line= 2
2197037.99695137394075.420991994 2197074.5829266395007.955330806
#Sta/Elev= 30
       0 2356.45    16.2 2347.49    61.8  2325.9   125.9 2301.68   149.9 2290.89
   157.9 2289.09   181.9 2278.37   213.9 2266.07     278  2244.6   374.6 2215.58
   406.1 2203.62   414.1 2199.73   438.1 2182.08   454.1 2172.98   462.1 2171.47
   518.2 2176.28   530.2 2175.81  544.392173.213   552.12173.278   562.3 2176.09
   578.2 2175.21   594.2 2176.92   610.2 2176.85     624 2181.29   642.3 2189.23
   674.3 2206.29   822.4 2290.67   866.6    2317   886.4 2327.52   933.3  2356.6
#Mann= 3 ,-1,0
       0      .1       0  544.39    .045       0   552.1      .1       0
#XS Ineff= 2 , 0
                          567.39         2182.74
Permanent Ineff=
       F       F
Bank Sta=544.39,552.1
XS Rating Curve= 0 ,0
Exp/Cntr=0.3,0.1

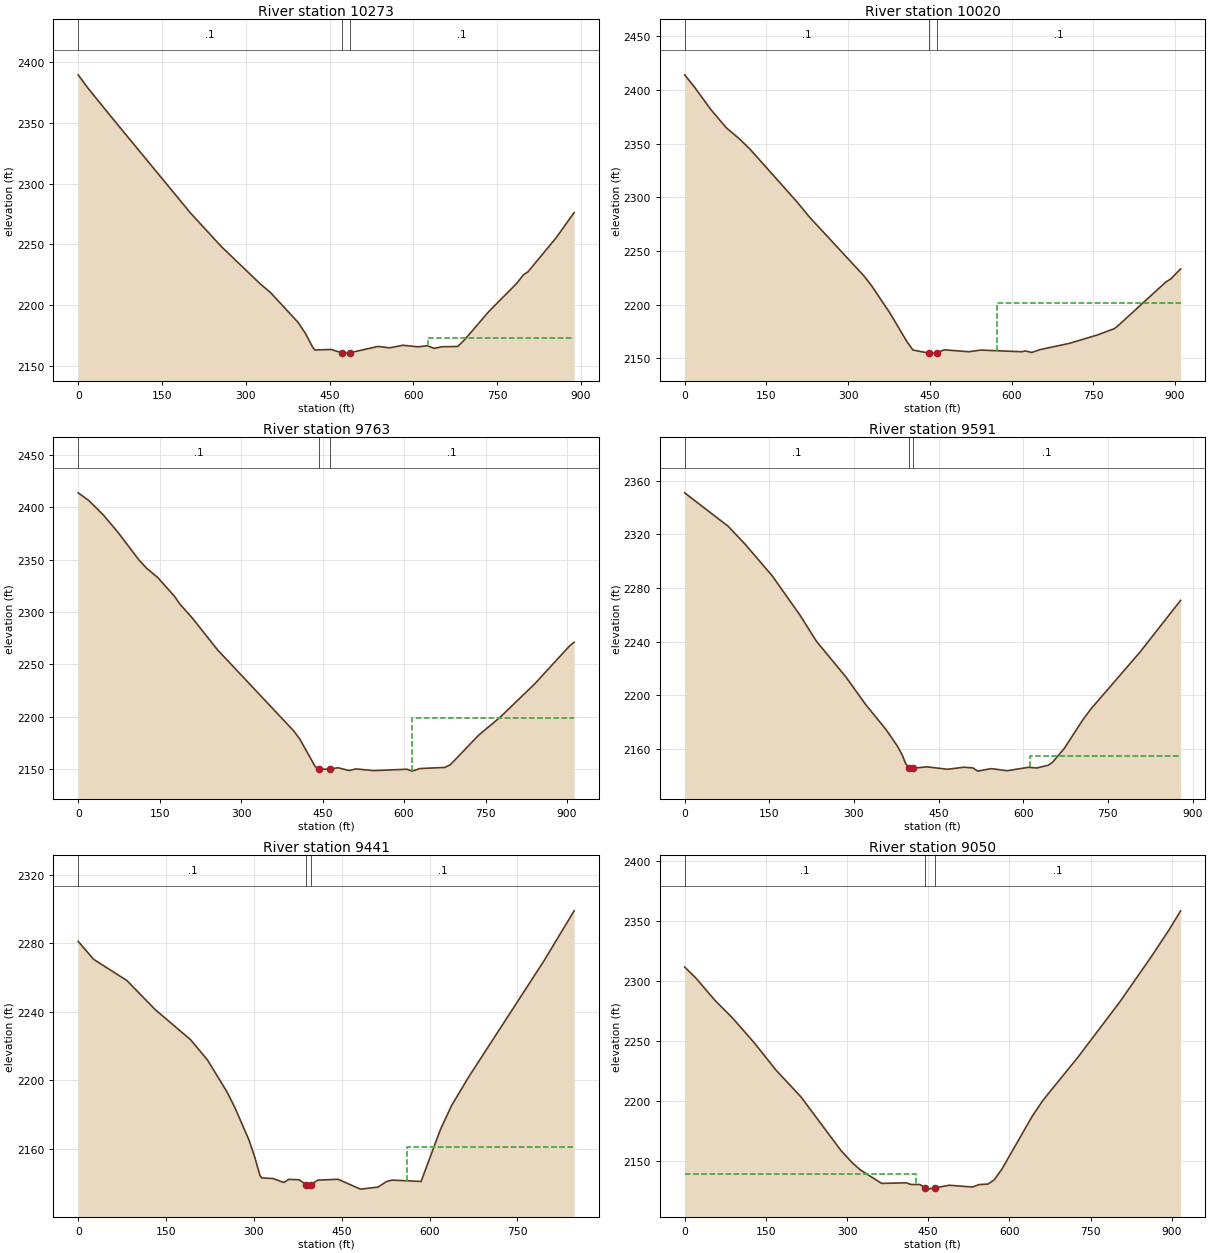
Type RM Length L Ch R = 1 ,10273   ,251,253,257
XS GIS Cut Line= 2
2196873.67373352394013.2941630572196606.13181594394859.899409086
#Sta/Elev= 30
       0 2389.72    16.7 2379.23    58.5 2355.48   201.2 2275.83   256.1 2248.35
   326.2 2217.41   343.9 2210.63   393.2  2186.1   406.8 2176.74   419.4 2165.73
   423.6 2163.08   452.9 2163.55  471.382160.852   473.9 2160.52   486.5 2160.85
   536.8 2166.02   557.8 2164.88   581.3 2167.02   608.2 2165.71   624.9 2166.59
   637.5 2164.43   650.1 2165.75   679.5 2166.02   692.1 2171.71   735.1 2194.79
   785.3 2218.09   796.9 2224.92   805.3 2227.52   855.7 2255.55   887.9 2276.31
#Mann= 3 ,-1,0
       0      .1       0  471.38    .045       0   486.5      .1       0
#XS Ineff= 2 , 0
                           625.9         2172.86
Permanent Ineff=
       F       F
Bank Sta=471.38,486.5
XS Rating Curve= 0 ,0
Exp/Cntr(USF)=0,0
Exp/Cntr=0.3,0.1

Type RM Length L Ch R = 1 ,10020   ,255.8,256.7,257
XS GIS Cut Line= 3
2196757.53602781393960.9868166872196510.79802781394343.460816687
2196283.47802781394737.754816687
#Sta/Elev= 30
       0 2414.25    17.3 2403.33    47.8 2382.05    76.3 2364.98   100.2  2354.7
   119.8 2345.07   206.6 2295.63   228.7 2281.94   328.7 2227.13   342.6 2218.12
   376.3 2192.69   408.3 2165.39   419.1 2157.84   447.7  2155.1   457.1 2154.97
   462.72155.065   476.4 2158.04   521.8 2156.28   543.3 2157.81   618.7 2156.27
   625.3 2157.02   637.2 2155.56   651.6 2158.18   706.5 2164.12   757.3 2171.85
   788.8 2177.82   794.2 2179.91     883 2221.15   891.8 2223.93   910.3  2233.4
#Mann= 3 ,-1,0
       0      .1       0   447.7    .045       0   462.7      .1       0
#XS Ineff= 2 , 0
                          572.96         2201.93
Permanent Ineff=
       F       F
Bank Sta=447.7,462.7
XS Rating Curve= 0 ,0
Exp/Cntr=0.3,0.1

Type RM Length L Ch R = 1 ,9763    ,169.7,172.5,172.1
XS GIS Cut Line= 2
2196530.37399675393846.0545961852196050.49457829394622.969580171
#Sta/Elev= 30
       0 2413.75    19.4 2406.45      46 2392.79    72.7  2376.4   111.8 2349.63
   125.9 2341.73   146.3 2332.91   177.6 2314.75     187  2307.6   210.2 2294.07
   256.7 2263.67   396.4 2186.57     408 2178.58   436.2 2152.35   442.7 2149.84
   463.1 2149.76   478.5 2151.12   498.9 2148.46   511.4    2150   544.3 2148.39
   605.5 2149.69   614.9 2147.89     629 2150.35   675.2 2151.43   685.4 2154.11
   737.1 2182.11     777 2199.44   840.9  2231.4   904.8 2267.55   913.2 2271.02
#Mann= 3 ,-1,0
       0      .1       0   442.7    .045       0   463.1      .1       0
#XS Ineff= 2 , 0
                          614.44         2198.44
Permanent Ineff=
       F       F
Bank Sta=442.7,463.1
XS Rating Curve= 0 ,0
Exp/Cntr=0.3,0.1

Type RM Length L Ch R = 1 ,9591    ,150,150,150.4
XS GIS Cut Line= 4
2196385.47228692 393809.789042012196105.61967236394213.778613989
2196080.57449674394393.4505260552195976.03811154394570.944596763
#Sta/Elev= 30
       0 2350.84    77.1 2325.93   106.9 2312.69     155 2289.11   204.6 2259.66
   233.3 2240.47   286.4 2213.42   320.4 2193.44     357 2174.53   377.1 2162.25
   385.7 2155.49   391.4 2149.51   398.3 2145.73   404.2 2145.75   428.8  2146.9
   465.9 2145.06   494.9 2146.61     511 2146.04   519.1 2143.68   543.3 2145.56
   571.6 2143.97   609.2 2146.53   624.1 2146.02   644.3 2148.07   651.7 2150.17
   672.6 2160.51     705 2181.47   719.7 2189.82   807.2 2232.44   878.9 2270.79
#Mann= 3 ,-1,0
       0      .1       0   398.3    .045       0   404.2      .1       0
#XS Ineff= 2 , 0
                             612            2155
Permanent Ineff=
       F       F
Bank Sta=398.3,404.2
XS Rating Curve= 0 ,0
Exp/Cntr(USF)=0,0
Exp/Cntr=0.3,0.1

Type RM Length L Ch R = 1 ,9441    ,389,390.6,391.7
XS GIS Cut Line= 2
2196234.74647665393763.0746299182195780.29171255394477.741396046
#Sta/Elev= 30
       0    2281    26.2 2270.55    83.1 2258.14   131.5 2241.17   192.1 2223.53
   220.7 2211.78   253.7 2193.36   267.1  2184.3   291.6 2165.08   301.1 2155.46
   310.5 2144.24   313.4 2142.91   332.8 2142.55   351.1 2140.25   359.8 2142.08
   377.2 2141.82  389.71 2138.93   397.5 2138.95   409.1 2141.63   443.8 2142.12
   481.9 2136.37   511.7 2137.52   526.6 2140.82   536.6 2141.64   585.5 2140.84
   618.7  2171.3   637.7 2185.23   666.9 2201.92     795 2269.43   846.9 2298.83
#Mann= 3 ,-1,0
       0      .1       0  389.71    .045       0   397.5      .1       0
#XS Ineff= 2 , 0
                          562.21          2161.1
Permanent Ineff=
       F       F
Bank Sta=389.71,397.5
XS Rating Curve= 0 ,0
Exp/Cntr(USF)=0,0
Exp/Cntr=0.3,0.1

Type RM Length L Ch R = 1 ,9050    ,262.3,261.5,260.1
XS GIS Cut Line= 2
2195977.55394817393558.0412111252195427.79494817394291.108211125
#Sta/Elev= 30
       0 2311.62    20.4 2302.63    55.6 2283.98    88.9 2268.89     129 2248.14
   168.9 2225.47   214.7 2203.34   288.9 2158.37   308.9  2148.6   323.9 2142.48
   363.9    2131   408.7 2131.51   418.9 2130.05   434.7  2130.1   443.9  2127.4
   448.9 2126.22   463.2 2127.37   488.9 2129.47   531.8 2127.99   543.9 2130.03
   560.4 2130.43   571.8 2133.93   586.1 2142.93   642.3 2187.19   662.3 2200.59
   726.1 2236.08   803.9 2282.51   863.2    2321   894.7 2342.54   916.3 2358.57
#Mann= 3 ,-1,0
       0      .1       0   443.9    .045       0   463.2      .1       0
#XS Ineff= 2 , 0
          428.11 2139.17
Permanent Ineff=
       F       F
Bank Sta=443.9,463.2
XS Rating Curve= 0 ,0
Exp/Cntr=0.3,0.1