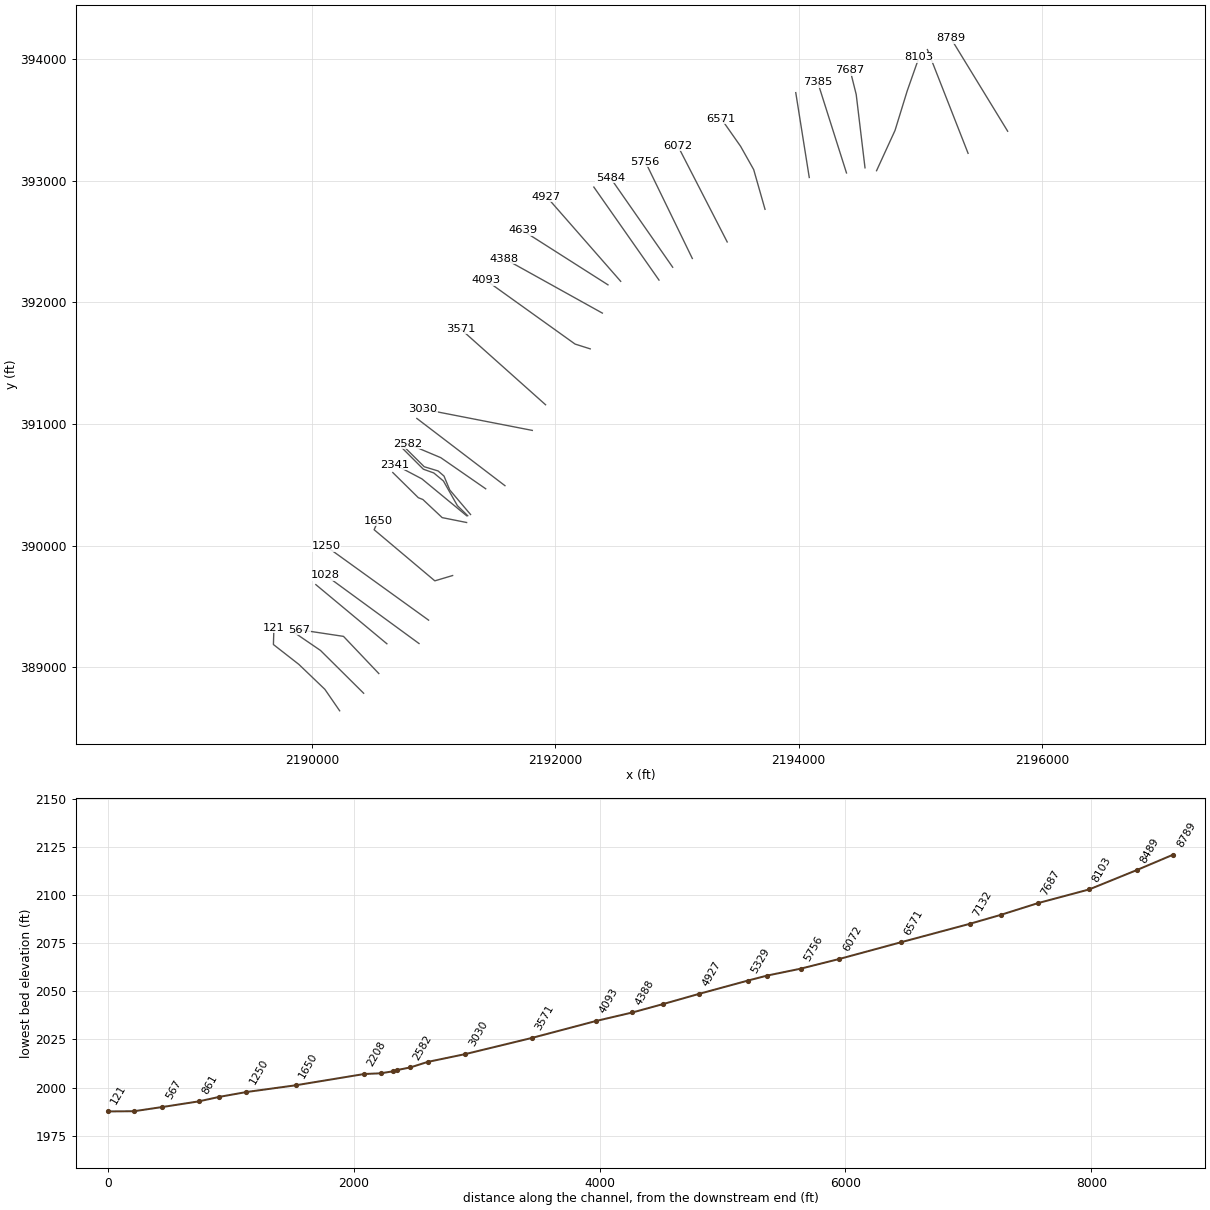
HEC-RAS study OLDHMRN.prj: OLDHMRN

--- OLDHMRN.g01 (geometry) --- (continued)

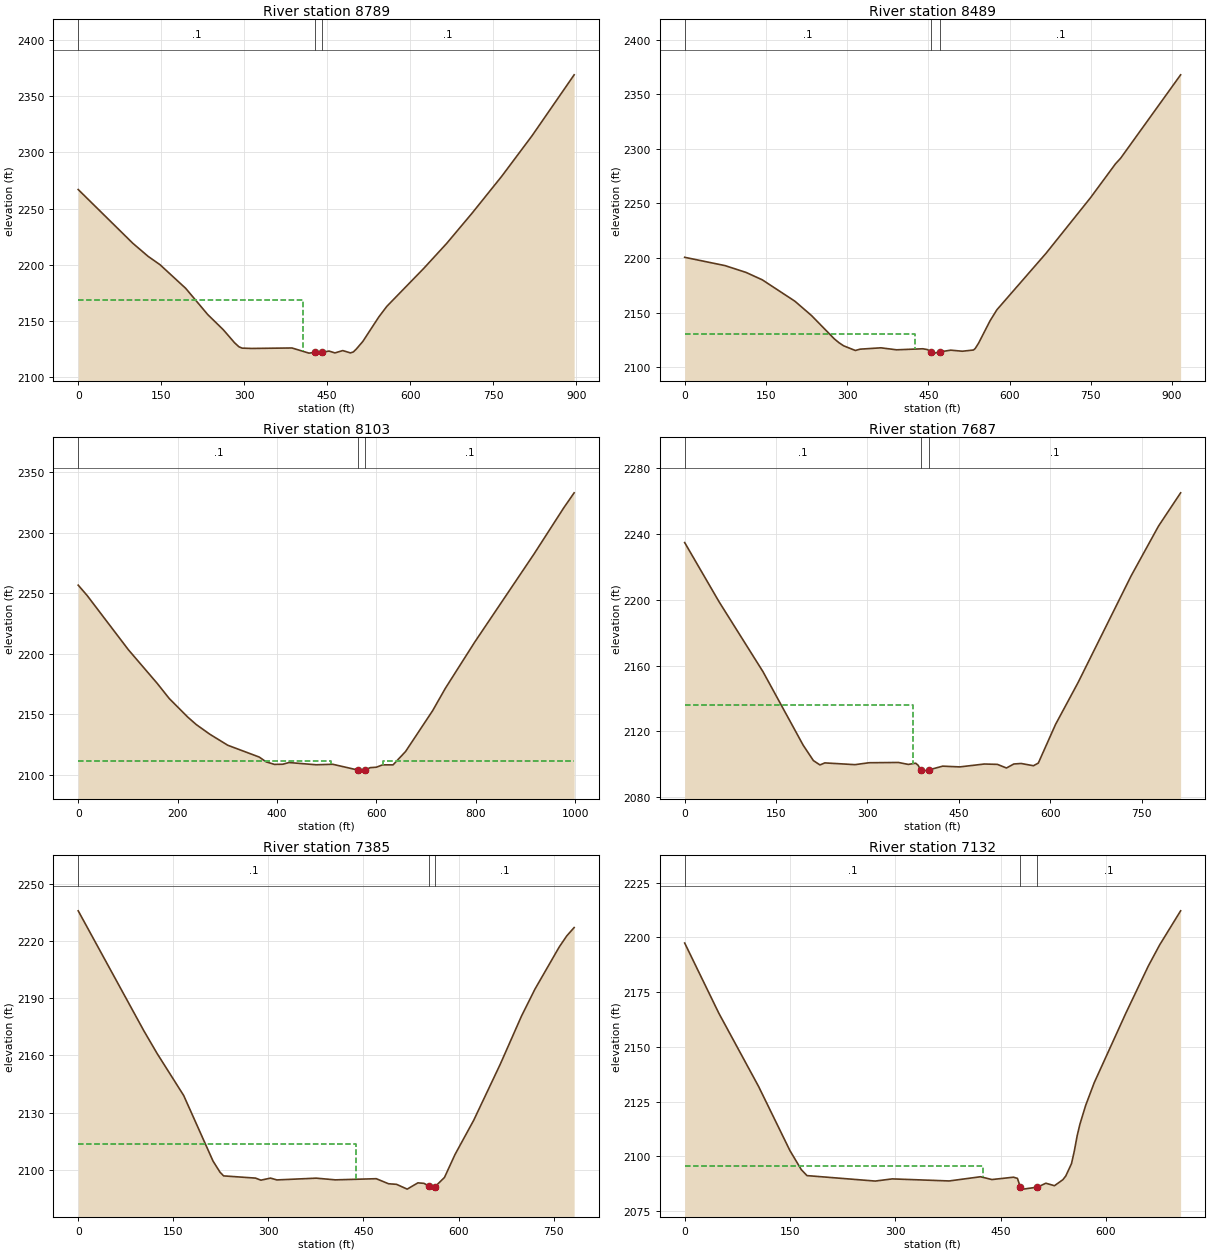
Type RM Length L Ch R = 1 ,8789    ,300.8,300,297.1
XS GIS Cut Line= 2
2195719.63779412393405.3461744792195251.91795087394170.030997566
#Sta/Elev= 30
       0 2266.92    98.6 2219.06   126.4 2207.34   147.9  2199.9   194.3 2178.84
   234.2 2155.44   262.4 2141.87   282.6 2130.35   290.5 2126.76   296.2 2125.57
   313.7 2125.28   386.4  2125.7   417.1 2121.11   428.3 2121.79   440.6 2121.85
   453.4 2122.94     464  2121.3   478.1 2123.38   492.1 2121.32   497.3 2122.17
   502.8 2124.82   514.4 2131.49   543.5 2153.47   557.8 2162.78     625 2196.86
   665.9 2218.84   712.3 2246.08   765.6  2278.8   820.4 2314.92   896.4 2369.15
#Mann= 3 ,-1,0
       0      .1       0   428.3    .045       0   440.6      .1       0
#XS Ineff= 2 , 0
          405.53 2168.38
Permanent Ineff=
       F       F
Bank Sta=428.3,440.6
XS Rating Curve= 0 ,0
Exp/Cntr(USF)=0,0
Exp/Cntr=0.3,0.1

Type RM Length L Ch R = 1 ,8489    ,393.7,385.2,377.1
XS GIS Cut Line= 2
2195394.12011036 393223.773649642195059.70911036 394076.43264964
#Sta/Elev= 30
       0  2200.7    74.6 2193.08   113.2 2186.88   143.3 2180.09   203.5 2160.53
   234.1 2147.46   276.5 2125.97   285.1 2122.48   293.7 2119.66   315.2 2115.41
   324.2 2116.62   362.4 2117.85   391.4 2116.03   439.8 2116.98   448.4 2116.22
   454.5 2114.24   461.2 2112.99   472.2  2114.2   491.3  2115.7   512.8 2114.73
   533.4 2115.85   536.5 2117.18   542.9 2122.22     564 2142.62   576.6 2152.67
   667.5 2204.45   749.5 2255.23   795.7  2286.3   805.1 2291.37   915.9 2367.71
#Mann= 3 ,-1,0
       0      .1       0   454.5    .045       0   472.2      .1       0
#XS Ineff= 2 , 0
          425.92 2130.13
Permanent Ineff=
       F       F
Bank Sta=454.5,472.2
XS Rating Curve= 0 ,0
Exp/Cntr=0.3,0.1

Type RM Length L Ch R = 1 ,8103    ,409.7,416.3,419.7
XS GIS Cut Line= 4
2194641.63313591393080.9487009652194793.61554833393412.415105187
2194893.48970506393736.644251674 2194990.9805974 394013.70543159
#Sta/Elev= 30
       0 2256.61    17.9 2248.08   100.9 2203.27   158.7 2175.57   183.1 2162.97
   220.3 2147.64   237.4 2141.47   264.6  2133.5   300.8 2124.36   364.1 2114.61
     378 2110.64   394.7 2108.55   411.5 2108.67     424 2110.08   478.5 2108.23
   511.9 2108.65   563.6 2103.78   570.5 2102.98   577.2 2103.88   587.3 2105.84
   599.8 2106.23   612.4 2108.17   633.3 2108.16   658.5 2119.19     713 2152.96
   738.4 2171.31   797.4 2209.45   916.9 2282.36   977.1 2320.74   997.6 2332.87
#Mann= 3 ,-1,0
       0      .1       0   563.6    .045       0   577.2      .1       0
#XS Ineff= 2 , 0
          507.61 2111.46  613.65         2111.64
Permanent Ineff=
       F       F
Bank Sta=563.6,577.2
XS Rating Curve= 0 ,0
Exp/Cntr(USF)=0,0
Minor Loss Coefficient=0
Exp/Cntr=0.3,0.1

Type RM Length L Ch R = 1 ,7687    ,299.6,301.8,300.2
XS GIS Cut Line= 3
2194546.62612375393104.6691323912194474.24090992393707.879247691
2194424.12806957393908.330609083
#Sta/Elev= 30
       0 2234.73    56.6 2198.68   128.6 2156.26   194.6 2111.59   211.3 2102.27
   222.1 2099.62   230.1 2100.86   279.6 2099.79   302.7 2100.96     351 2101.12
   367.1 2099.94   379.2 2100.68   383.2 2099.44   387.3 2096.64   391.3 2095.86
   401.9 2096.71   423.5 2098.88   451.7 2098.43     492 2100.18   513.4 2099.96
   528.3 2097.77   540.4  2100.2   552.4  2100.5   572.6 2099.14   580.6 2100.76
   608.9 2124.27     646 2149.79   732.9 2214.47   777.9 2244.74   814.2 2264.96
#Mann= 3 ,-1,0
       0      .1       0   387.3    .045       0   401.9      .1       0
#XS Ineff= 2 , 0
          374.81 2136.25
Permanent Ineff=
       F       F
Bank Sta=387.3,401.9
XS Rating Curve= 0 ,0
Exp/Cntr(USF)=0,0
Exp/Cntr=0.3,0.1

Type RM Length L Ch R = 1 ,7385    ,254.3,253.5,249.7
XS GIS Cut Line= 2
2194394.37341524393062.4778245242194157.78009316 393808.22646999
#Sta/Elev= 30
       0 2236.03   103.5 2173.02   124.5 2161.04   166.4 2138.98   212.7 2104.51
   223.7 2098.68   229.4 2096.73   279.8 2095.56   288.2 2094.48   303.4 2095.56
   313.4 2094.61   375.7 2095.53   405.7 2094.64   470.2 2095.25   489.6 2092.59
   502.2 2092.29     519 2089.77   535.9 2093.07   545.5 2092.81     554 2091.18
   562.8 2091.02   577.8 2095.89   594.5    2108   623.9 2125.94   665.9 2155.47
   699.4 2180.77   720.4 2194.78   758.9 2217.05   770.8 2222.89   782.4 2227.24
#Mann= 3 ,-1,0
       0      .1       0     554    .045       0   562.8      .1       0
#XS Ineff= 2 , 0
          438.71 2113.24
Permanent Ineff=
       F       F
Bank Sta=554,562.8
XS Rating Curve= 0 ,0
Exp/Cntr=0.3,0.1

Type RM Length L Ch R = 1 ,7132    ,552,560.4,564.6
XS GIS Cut Line= 2
2194088.23985896 393025.155128222193977.28497279 393722.71276487
#Sta/Elev= 30
       0 2197.41    48.6  2165.4   105.3 2131.92   149.9 2102.68   166.1 2093.98
   174.2 2091.26   271.4 2088.77   295.7 2089.76   376.7 2088.82   421.3 2090.74
   437.5 2089.46   468.3 2090.53   473.9    2090478.09892085.958     482 2085.09
502.3988 2085.99   514.4 2087.79   526.6 2086.65   538.7 2089.41   542.8 2091.12
   550.9 2096.72   554.9 2102.45     559  2109.5     563 2114.85   571.1 2123.34
   583.3 2133.69   627.8 2165.05   660.2 2186.85   676.4 2196.52   706.3  2212.1
#Mann= 3 ,-1,0
       0      .1       0478.0989    .045       0502.3988      .1       0
#XS Ineff= 2 , 0
          425.46 2095.59
Permanent Ineff=
       F       F
Bank Sta=478.0989,502.3988
XS Rating Curve= 0 ,0
Exp/Cntr=0.3,0.1

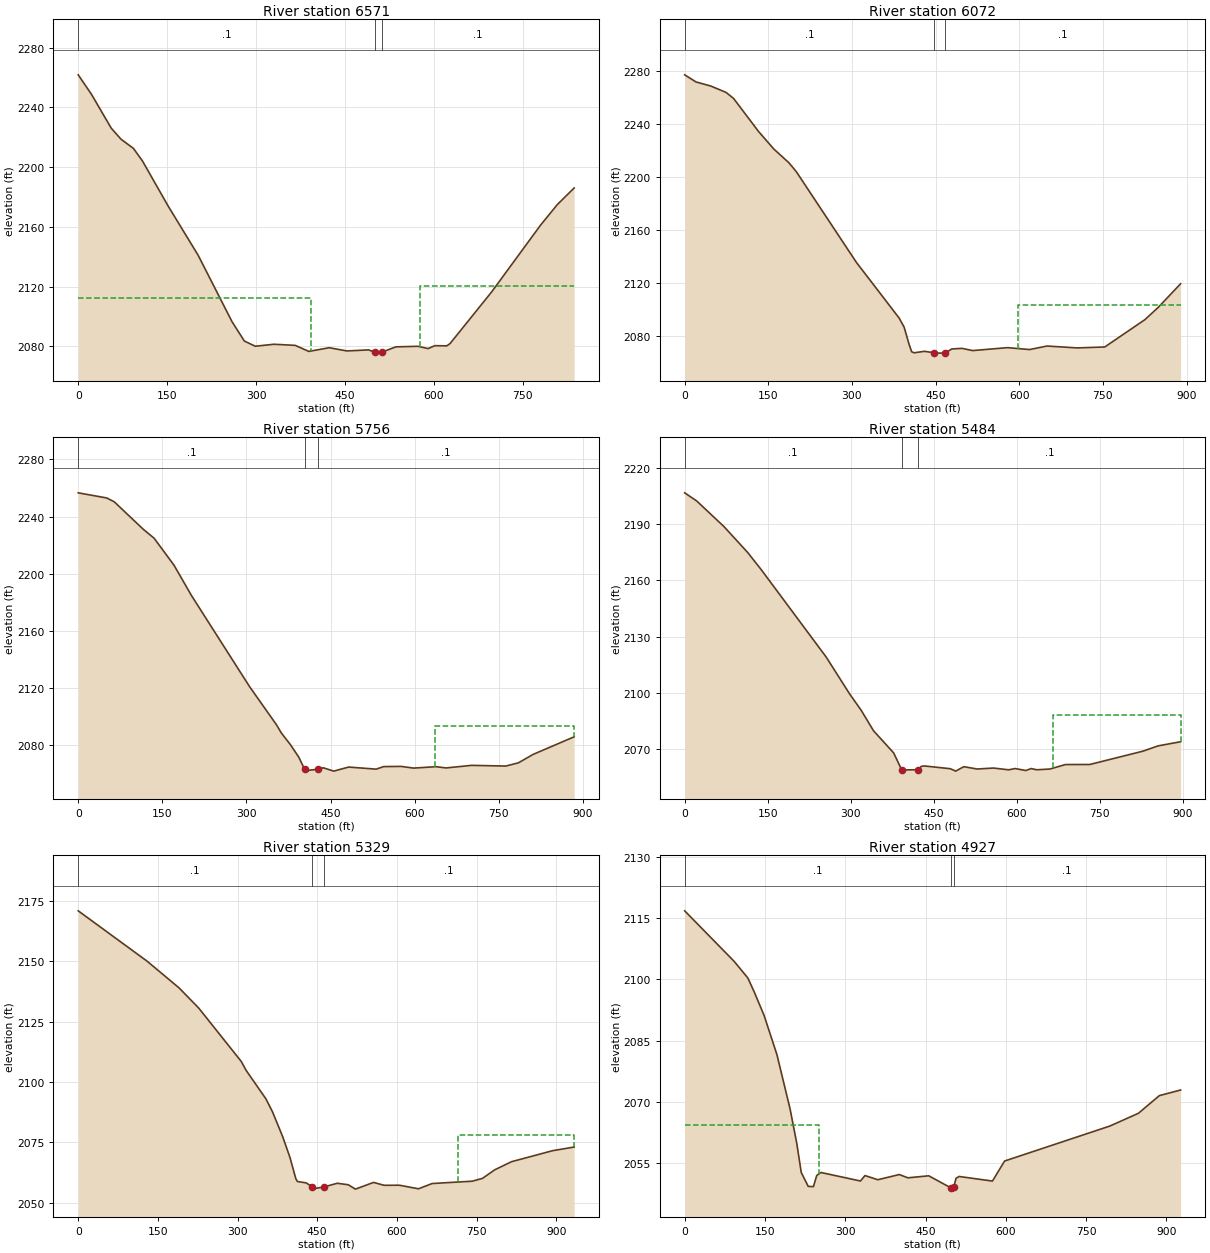
Type RM Length L Ch R = 1 ,6571    ,499.5,499.7,495.6
XS GIS Cut Line= 4
2193724.53586735392763.6189635132193631.46643745393089.873841797
2193523.96691223393280.9841088512193364.32827903393508.515782583
#Sta/Elev= 30
       0 2261.75    22.4 2248.69    55.7 2226.05    72.3 2218.63    93.1 2212.53
   108.4 2204.09   151.4 2174.13   202.2 2141.07   259.5 2096.49   280.3 2083.56
   298.6 2080.11   330.2 2081.43     366 2080.68     389 2076.63   423.4 2079.11
   453.2 2076.95   489.9 2077.66   499.8 2076.11   508.3 2075.49   512.9 2076.26
   535.8 2079.68   572.9 2080.06   590.1 2078.53   601.6 2080.47   621.7 2080.36
   627.2 2081.89   697.5 2116.54   779.6 2161.02     808 2174.86   836.5 2186.03
#Mann= 3 ,-1,0
       0      .1       0   499.8    .045       0   512.9      .1       0
#XS Ineff= 2 , 0
          393.24  2112.5  576.04         2120.31
Permanent Ineff=
       F       F
Bank Sta=499.8,512.9
XS Rating Curve= 0 ,0
Exp/Cntr=0.3,0.1

Type RM Length L Ch R = 1 ,6072    ,315.2,315.3,314
XS GIS Cut Line= 2
2193413.64422452392495.2738867252193006.95060658393286.146451075
#Sta/Elev= 30
       0 2276.93    20.3 2271.56    47.1 2268.43    74.1 2263.68    87.6 2259.15
   132.6 2234.09   159.9  2220.9   186.9 2210.55     200 2203.92     308  2135.3
   384.5 2093.35   393.5 2086.47   402.5 2073.34     407 2067.87   411.4 2067.09
   430.2  2068.2   447.52067.068   456.4 2066.83   467.32066.953   478.9 2069.96
   496.9 2070.44   516.4 2068.75   578.8 2070.97   618.4 2069.53   649.8 2072.19
   703.8 2070.77   753.3 2071.47   825.3 2092.12   849.1 2101.33   889.3 2119.21
#Mann= 3 ,-1,0
       0      .1       0   447.5    .045       0   467.3      .1       0
#XS Ineff= 2 , 0
                          597.54         2103.41
Permanent Ineff=
       F       F
Bank Sta=447.5,467.3
XS Rating Curve= 0 ,0
Exp/Cntr=0.3,0.1

Type RM Length L Ch R = 1 ,5756    ,267.9,272.7,272.1
XS GIS Cut Line= 2
2193126.86228344392359.3958020872192740.20923817393154.691639265
#Sta/Elev= 30
       0 2256.63    50.9 2253.03    64.3 2250.34   115.9 2231.15   135.4 2224.82
   170.8 2205.97   202.1 2184.63   305.6  2120.9   353.5 2094.25   362.2  2088.5
   378.9 2080.03   393.4 2071.48   402.3 2064.21   404.9 2062.95   407.4 2062.21
     427 2063.08   437.3 2064.08   455.6 2061.77   482.2 2064.62   531.3 2063.16
   544.6 2064.95   575.7 2065.08     598 2063.89     638 2064.88   655.9    2064
   701.4 2065.81   762.5 2065.32   784.8 2067.56   811.2 2073.49   884.3  2085.8
#Mann= 3 ,-1,0
       0      .1       0   404.9    .045       0     427      .1       0
#XS Ineff= 2 , 0
                          635.94          2093.2
Permanent Ineff=
       F       F
Bank Sta=404.9,427
XS Rating Curve= 0 ,0
Exp/Cntr(USF)=0,0
Exp/Cntr=0.3,0.1

Type RM Length L Ch R = 1 ,5484    ,156.1,155,155.2
XS GIS Cut Line= 2
  2192965.462693 392287.399612152192453.18100493393022.643278455
#Sta/Elev= 30
       0 2206.69    21.7 2202.36    71.2 2188.62   114.3  2174.7   138.7 2165.55
   255.7 2119.05   298.1 2099.36   319.1 2090.57   341.2 2079.73   377.6 2067.91
   392.2  2058.8   422.1 2058.93   427.4  2060.7   433.2 2060.94   479.9 2059.47
   489.7 2058.18   504.3 2060.55   528.7  2059.3   557.9 2059.83   585.5 2058.88
     597 2059.56   616.4 2058.51   626.2 2059.55   635.9  2058.9     660  2059.3
     688 2061.69     732 2061.72   827.9 2068.82   855.3 2071.64   896.1 2073.87
#Mann= 3 ,-1,0
       0      .1       0   392.2    .045       0   422.1      .1       0
#XS Ineff= 2 , 0
                          665.13         2087.98
Permanent Ineff=
       F       F
Bank Sta=392.2,422.1
XS Rating Curve= 0 ,0
Exp/Cntr(USF)=0,0
Exp/Cntr=0.3,0.1

Type RM Length L Ch R = 1 ,5329    ,401.4,401.4,392.1
XS GIS Cut Line= 2
 2192852.8280268392181.669576737 2192317.1550268392946.449576737
#Sta/Elev= 30
       0 2170.86   129.4 2150.06   189.9 2138.94     227 2130.56   307.1 2108.44
     316 2104.83   353.4 2092.99   365.7 2087.66     385 2077.31   398.6 2068.78
   409.6    2060   412.5 2058.77   429.2 2058.19   440.4 2056.57   447.4 2055.92
   462.5  2056.5   487.8 2058.03   508.5 2057.41   521.9  2055.6   556.1 2058.38
   575.7 2057.19     605 2057.21   640.6 2055.74   666.4 2057.92   741.7 2058.88
   761.2 2060.06   784.2 2063.61   815.8 2066.96   893.1 2071.52   933.7 2073.03
#Mann= 3 ,-1,0
       0      .1       0   440.4    .045       0   462.5      .1       0
#XS Ineff= 2 , 0
                          714.29         2078.09
Permanent Ineff=
       F       F
Bank Sta=440.4,462.5
XS Rating Curve= 0 ,0
Exp/Cntr=0.3,0.1

Type RM Length L Ch R = 1 ,4927    ,283.8,288.3,288.2
XS GIS Cut Line= 2
2192537.90386563392171.5903782912191927.51443695392868.456929528
#Sta/Elev= 30
       0 2116.75    92.5 2104.37     118 2100.31   129.9  2096.9   148.3 2091.16
   172.3 2081.56   196.9 2068.25   209.3  2059.9   217.8 2052.68   230.8 2049.29
   240.5 2049.23   246.7 2051.96   254.6 2052.69   328.3 2050.61   336.8 2051.94
   360.8 2050.92   400.9 2052.19   416.9 2051.39   455.9 2051.88   496.6 2048.98
   500.4 2048.62  502.482049.046   506.9 2051.28   512.6 2051.72   574.9 2050.59
   597.6  2055.5   794.4 2064.07   847.6 2067.19   886.7 2071.51   926.4 2072.89
#Mann= 3 ,-1,0
       0      .1       0   496.6    .045       0  502.48      .1       0
#XS Ineff= 2 , 0
          250.38 2064.26
Permanent Ineff=
       F       F
Bank Sta=496.6,502.48
XS Rating Curve= 0 ,0
Exp/Cntr=0.3,0.1

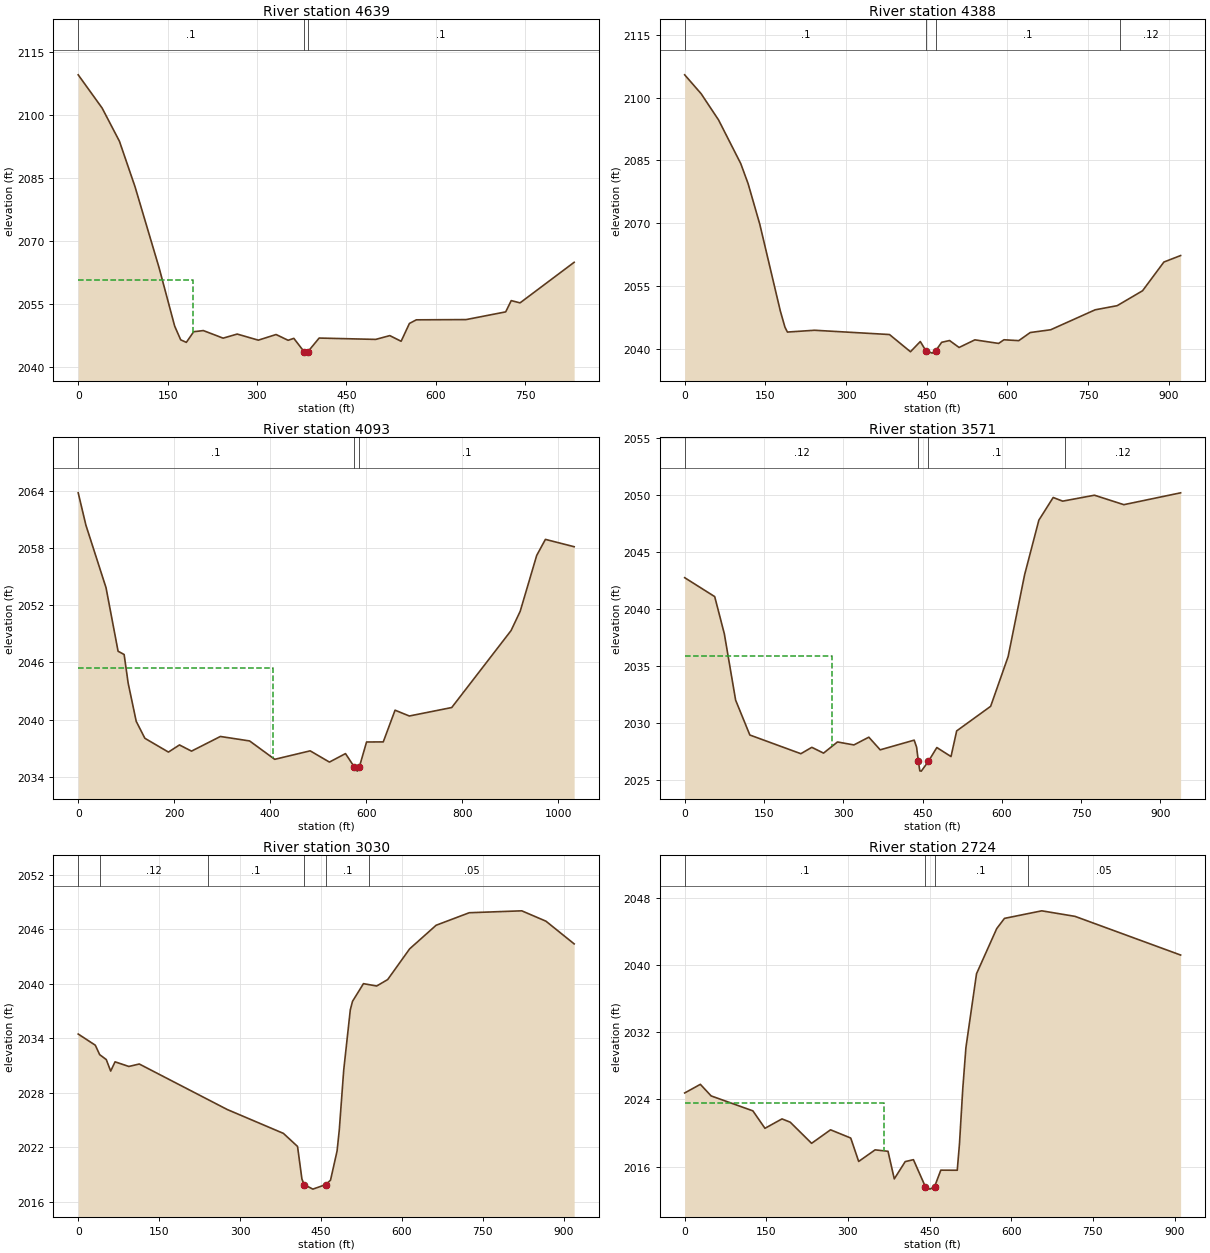
Type RM Length L Ch R = 1 ,4639    ,250.3,251,251.3
XS GIS Cut Line= 2
2192433.27368544392142.7397572272191731.20888495392589.990868319
#Sta/Elev= 30
       0 2109.51    40.2  2101.6    69.2 2093.73    95.3 2082.95   135.8 2063.65
   161.9 2049.81     172 2046.55   181.5 2045.95   193.8 2048.47     210 2048.75
   243.2 2046.95   266.9 2047.92   302.3 2046.47   332.1 2047.81   352.3 2046.44
   361.9  2046.9   379.2 2043.72   382.1 2043.39   385.5 2043.73   404.4 2046.97
   499.3 2046.65     523 2047.55     542 2046.21   555.9 2050.44   567.5  2051.3
   651.1 2051.36   717.5 2053.19   726.8 2055.87   741.6 2055.33   832.4 2064.97
#Mann= 3 ,-1,0
       0      .1       0   379.2    .045       0   385.5      .1       0
#XS Ineff= 2 , 0
          192.01 2060.72
Permanent Ineff=
       F       F
Bank Sta=379.2,385.5
XS Rating Curve= 0 ,0
Exp/Cntr(USF)=0,0
Exp/Cntr=0.3,0.1

Type RM Length L Ch R = 1 ,4388    ,296,294.7,293.4
XS GIS Cut Line= 2
2192387.23802781391910.3344922872191581.05202781392358.257492287
#Sta/Elev= 30
       0 2105.45    30.6 2100.94      63 2094.68   104.2 2084.28   117.9 2079.49
   139.7 2069.77   177.9 2049.05   186.5 2045.19   191.1 2044.03   241.5 2044.46
   380.9 2043.44   419.9 2039.33   438.2 2041.77   448.5 2039.59   460.3    2039
   467.1 2039.62   477.9 2041.58   492.6 2042.01   510.3 2040.35   539.7 2042.17
   583.8 2041.32   593.8 2042.19   621.3 2041.98   642.7 2043.92   680.7 2044.58
   763.3 2049.34   804.3 2050.33   851.5 2053.89   891.2 2060.75   922.3  2062.3
#Mann= 4 ,-1,0
       0      .1       0   448.5    .045       0   467.1      .1       0
     810     .12       0
Bank Sta=448.5,467.1
XS Rating Curve= 0 ,0
Exp/Cntr=0.3,0.1

Type RM Length L Ch R = 1 ,4093    ,522.4,522,517.4
XS GIS Cut Line= 3
2192287.42921214391616.3079011372192162.97838861391655.723909284
     2191428.681      392181.264
#Sta/Elev= 30
       0 2063.82      16 2060.43      58 2053.85    83.1 2047.18    95.7 2046.84
   104.1 2043.83   120.9 2039.82   138.9 2038.04     188 2036.59     211 2037.34
   236.1 2036.69   296.3 2038.23   357.2 2037.76   409.5 2035.83   483.4 2036.72
   523.5 2035.54     557 2036.43   575.1 2035.05   581.6 2034.59586.04062035.058
   600.9 2037.65   635.7 2037.66   660.3 2040.99     690 2040.38   778.4 2041.27
     902 2049.35     921 2051.37   955.5 2057.25   973.6 2058.93  1033.5 2058.16
#Mann= 3 ,-1,0
       0      .1       0   575.1    .045       0586.0406      .1       0
#XS Ineff= 2 , 0
          405.53 2045.38
Permanent Ineff=
       F       F
Bank Sta=575.1,586.0406
XS Rating Curve= 0 ,0
Exp/Cntr=0.3,0.1

Type RM Length L Ch R = 1 ,3571    ,523.8,540.9,546.6
XS GIS Cut Line= 2
     2191920.165      391157.024     2191220.043      391781.669
#Sta/Elev= 30
       0 2042.75    56.8 2041.09      75 2037.83    96.4    2032   123.3 2028.94
   219.8  2027.3   240.6 2027.86   262.7 2027.35   289.1 2028.33   320.2 2028.07
   348.4 2028.75   369.9 2027.64   434.2 2028.49   438.8 2027.87   442.1 2026.64
   444.9 2025.79   447.7 2025.77     461 2026.62   477.1 2027.84   503.9 2027.05
   514.6  2029.3   578.9 2031.46     612 2035.83   643.1    2043   670.1  2047.8
   697.2 2049.79   715.2 2049.47   775.3 2049.99   830.9 2049.16   938.3  2050.2
#Mann= 4 ,-1,0
       0     .12       0   442.1    .045       0     461      .1       0
     720     .12       0
#XS Ineff= 2 , 0
          279.57 2035.92
Permanent Ineff=
       F       F
Bank Sta=442.1,461
XS Rating Curve= 0 ,0
Exp/Cntr=0.3,0.1

Type RM Length L Ch R = 1 ,3030    ,319.1,306.2,299.7
XS GIS Cut Line= 2
2191811.25308445390946.0799011372190908.82808445391122.002901137
#Sta/Elev= 30
       0 2034.46    31.7 2033.23    39.8 2032.19      52 2031.65    60.2 2030.38
    68.3  2031.4    93.9 2030.89   113.2 2031.16   276.2 2026.15   380.4 2023.52
   406.6 2022.08   414.7  2018.5   418.8 2017.88     435 2017.38   458.9 2017.88
   467.7 2018.36   479.9 2021.58     484  2023.9   492.2 2030.48   504.4 2037.12
   508.5 2038.06   528.8 2040.01   553.3 2039.75   573.7 2040.46   614.4 2043.84
   663.5 2046.44   724.9 2047.82   822.3 2048.03   867.1 2046.89   919.4 2044.39
#Mann= 6 ,-1,0
       0      .1       0      40     .12       0     240      .1       0
   418.8    .045       0   458.9      .1       0     540     .05       0
Bank Sta=418.8,458.9
XS Rating Curve= 0 ,0
Exp/Cntr=0.3,0.1

Type RM Length L Ch R = 1 ,2724    ,142.9,141.8,141.8
XS GIS Cut Line= 2
2191586.32787434390491.7198321132190861.97587434391044.466832113
#Sta/Elev= 30
       0 2024.77    28.8  2025.8    48.6 2024.42   125.3 2022.64   147.5 2020.56
   178.8 2021.68   193.9 2021.29   233.2 2018.77     268 2020.38   305.1  2019.4
   319.7 2016.61   349.9 2017.99   373.6 2017.82   385.1 2014.53   405.2 2016.59
   420.3 2016.82   442.1 2013.62   450.6 2013.31     4592013.585   470.6 2015.57
   500.8 2015.56   504.9 2018.71   510.9 2025.22   516.7 2030.16   536.2 2038.98
   573.3 2044.36   587.6 2045.58   656.1 2046.48   717.2 2045.82   911.2 2041.21
#Mann= 4 ,-1,0
       0      .1       0   442.1    .045       0     459      .1       0
     630     .05       0
#XS Ineff= 2 , 0
          367.13  2023.6
Permanent Ineff=
       F       F
Bank Sta=442.1,459
XS Rating Curve= 0 ,0
Exp/Cntr=0.3,0.1

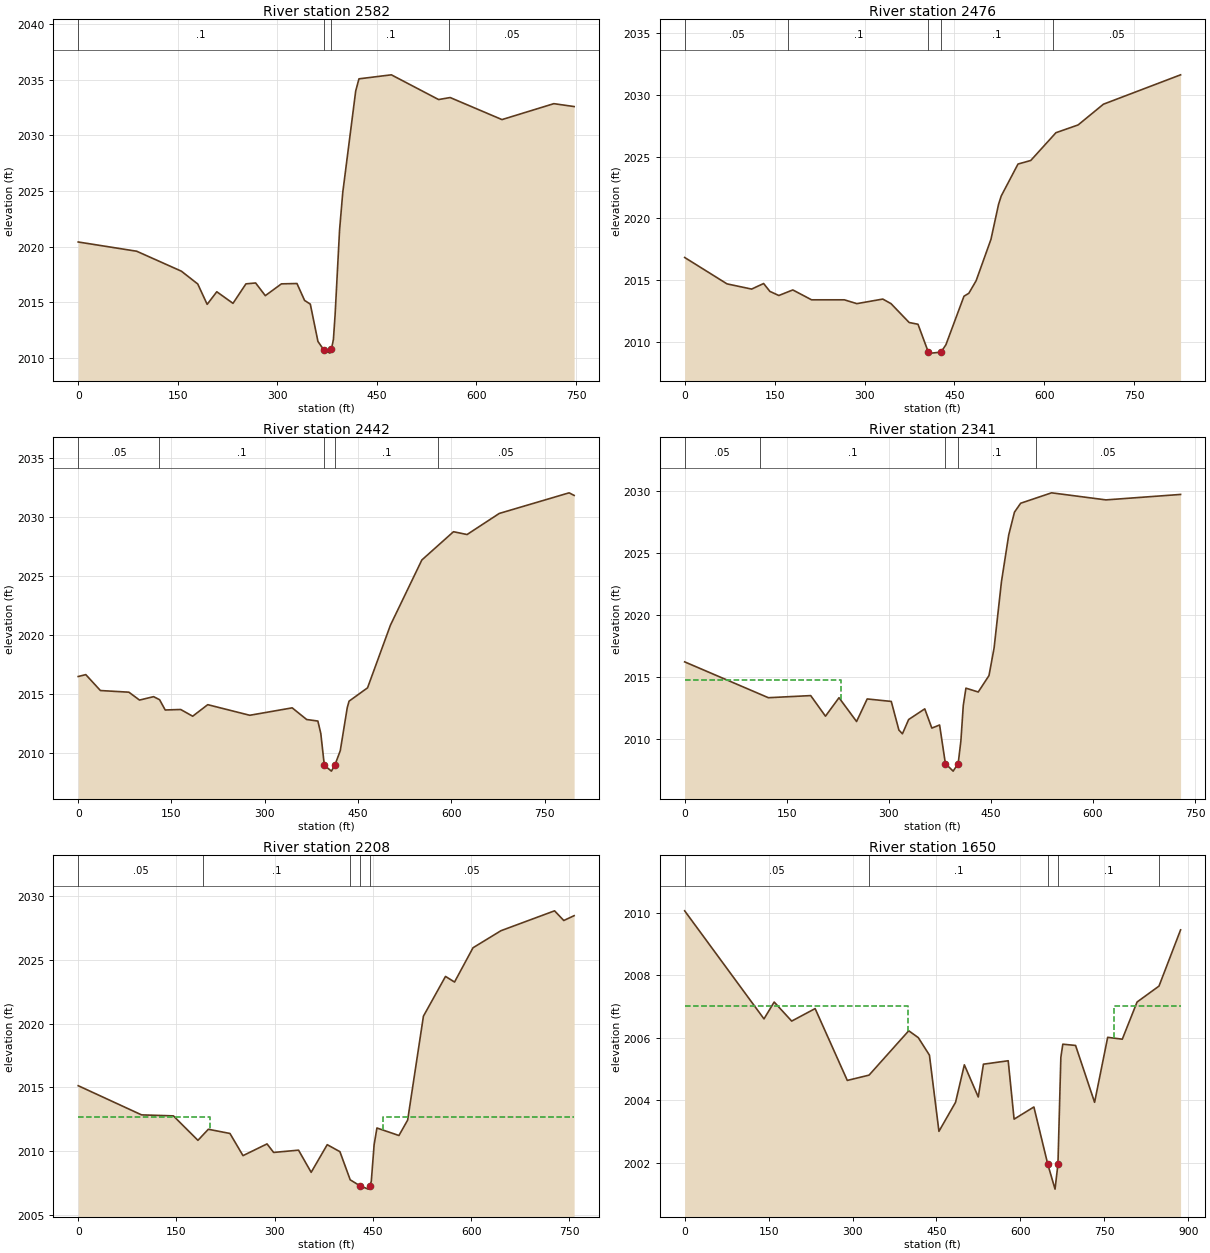
Type RM Length L Ch R = 1 ,2582    ,108.7,106,104.7
XS GIS Cut Line= 3
2191427.93087888390466.3072564922191058.46009243390722.094724034
2190784.05208128390837.738100163
#Sta/Elev= 30
       0 2020.41    88.1 2019.58   155.4 2017.79   180.1 2016.64   194.3 2014.81
   208.8 2015.94   233.2  2014.9   252.7 2016.65   267.3 2016.73   281.9 2015.59
   306.2 2016.65   329.6 2016.68   341.1 2015.16   349.7 2014.83   361.2 2011.48
   369.9 2010.73   379.2 2010.43   381.4 2010.76   384.5 2011.65   387.1 2013.91
   393.8  2021.5   398.6 2024.86   418.1 2033.97     423 2035.06   471.8 2035.42
     543  2033.2   560.4 2033.38   638.5  2031.4   716.6 2032.83   747.2 2032.57
#Mann= 4 ,-1,0
       0      .1       0   369.9    .045       0   381.4      .1       0
  559.37     .05       0
Bank Sta=369.9,381.4
XS Rating Curve= 0 ,0
Exp/Cntr(USF)=0,0
Exp/Cntr=0.3,0.1

Type RM Length L Ch R = 1 ,2476    ,34.5,34.8,35
XS GIS Cut Line= 6
2191303.51253057390254.7368747822191132.37156138390456.696332674
2191085.16025954390570.7903121332191036.63753264390612.755913773
2190922.54355318390647.5086776312190742.87832116  390825.8624846
#Sta/Elev= 30
       0 2016.84    70.7  2014.7   111.7 2014.28   131.7 2014.73   142.2 2014.09
   157.1 2013.76   180.4 2014.21   211.7 2013.41   266.3 2013.41   287.2  2013.1
   330.5 2013.47   344.2  2013.1   374.5 2011.57   389.2 2011.43   406.4 2009.18
   411.7 2009.09   427.5 2009.17   435.7 2009.76   465.9  2013.7     474 2013.94
   486.2 2014.96   510.9 2018.31   523.6 2021.15     528 2021.82     556 2024.41
   577.3  2024.7   619.3 2026.95   656.3 2027.58   698.5 2029.26   827.2 2031.64
#Mann= 5 ,-1,0
       0     .05       0  172.97      .1       0   406.4    .045       0
   427.5      .1       0  614.01     .05       0
Bank Sta=406.4,427.5
XS Rating Curve= 0 ,0
Exp/Cntr(USF)=0,0
Exp/Cntr=0.3,0.1

Type RM Length L Ch R = 1 ,2442    ,100.4,100.2,100.9
XS GIS Cut Line= 6
2191280.56259217390244.2454743722191195.31996384390327.520965126
2191080.57027186390530.1361355442191001.22905626390596.363100632
 2190915.3307154390627.1815893362190739.59975853390802.912546204
#Sta/Elev= 30
       0 2016.45    12.2 2016.61    35.7 2015.26    81.5 2015.12    98.6 2014.45
   121.2 2014.74   130.9 2014.48   139.9 2013.61   164.8 2013.65   184.1 2013.08
   208.3 2014.06   275.9 2013.16   344.1 2013.79   367.4  2012.8   385.4 2012.67
   390.1 2011.62   395.8 2008.91   407.2 2008.42   412.8 2008.94   421.4 2010.15
   432.7 2013.82   435.6 2014.36   465.3 2015.49   502.1 2020.81   552.6 2026.34
   603.5 2028.74   625.3  2028.5   677.1 2030.29   789.4 2032.04   797.5 2031.82
#Mann= 5 ,-1,0
       0     .05       0  129.17      .1       0   395.8    .045       0
   412.8      .1       0  578.99     .05       0
Bank Sta=395.8,412.8
XS Rating Curve= 0 ,0
Exp/Cntr(USF)=0,0
Exp/Cntr=0.3,0.1

Type RM Length L Ch R = 1 ,2341    ,129.9,133.5,138.1
XS GIS Cut Line= 3
2191271.12630108390244.8207903452190903.61557185390547.649631228
2190680.16904848 390665.25306458
#Sta/Elev= 30
       0 2016.19     123  2013.3   185.2 2013.47   206.9 2011.81   226.8  2013.3
   252.6 2011.38   268.2  2013.2   303.6    2013   314.8 2010.69     320 2010.39
   329.1 2011.54   352.8  2012.4   363.2 2010.85   374.6  2011.1   383.1 2007.99
   394.5 2007.38   401.9 2007.99   405.9 2009.83   409.4 2012.68   413.3 2014.07
   431.4 2013.76   447.2 2015.09   454.7 2017.32   465.5 2022.66   476.2 2026.43
   484.6 2028.26   493.7 2028.98   539.1 2029.82   619.1 2029.25   728.7 2029.69
#Mann= 5 ,-1,0
       0     .05       0     110      .1       0   383.1    .045       0
   401.9      .1       0   516.2     .05       0
#XS Ineff= 2 , 0
          230.31 2014.74
Permanent Ineff=
       F       F
Bank Sta=383.1,401.9
XS Rating Curve= 0 ,0
Exp/Cntr(USF)=0,0
Exp/Cntr=0.3,0.1

Type RM Length L Ch R = 1 ,2208    ,561.2,558.1,552.5
XS GIS Cut Line= 5
2191271.03986745390189.0252792852191070.22043577390229.140332565
2190911.45580074390378.1046814782190874.21471351390392.805110647
2190664.22319974390599.565903376
#Sta/Elev= 30
       0 2015.14    96.7 2012.85   145.4 2012.77   182.8 2010.85   198.7 2011.72
   231.7 2011.39   251.6 2009.65   288.3 2010.57   298.4  2009.9   336.4 2010.08
   355.7 2008.34   380.2 2010.51   399.6 2009.96   415.3 2007.75429.83922007.292
   442.8 2007.02445.33882007.277   447.5 2007.64   451.8  2010.5   456.1 2011.82
   489.7 2011.23     503 2012.44   527.1  2020.6   560.8 2023.72   574.6 2023.28
   602.8 2025.97   645.5 2027.31   727.3 2028.87   741.4 2028.11   757.2 2028.49
#Mann= 5 ,-1,0
       0     .05       0     190      .1       0  414.79     .05       0
429.8392    .045       0445.3388     .05       0
#XS Ineff= 2 , 0
          201.01 2012.67  465.58          2012.7
Permanent Ineff=
       F       F
Bank Sta=429.8392,445.3388
XS Rating Curve= 0 ,0
Exp/Cntr=0.3,0.1

Type RM Length L Ch R = 1 ,1650    ,396.8,399.2,398.9
XS GIS Cut Line= 4
2191156.06581072 389753.091348212191009.73657067389709.488195825
2190510.75756454390129.6673193282190543.30431472390204.286697791
#Sta/Elev= 30
       0 2010.06   141.8  2006.6     160 2007.14   191.3 2006.53   233.2 2006.93
   290.7 2004.63   329.6  2004.8   400.5 2006.22   417.6    2006   437.5 2005.44
   454.5    2003   484.2 2003.93   499.9 2005.13   524.8  2004.1     534 2005.15
   578.3 2005.26   588.8 2003.39   624.2 2003.78     649 2001.95     662 2001.15
   667.2 2001.95   672.4 2005.37   675.9 2005.79   698.7 2005.75   732.7 2003.93
   756.1 2006.01   782.2 2005.95   808.6 2007.14   847.8 2007.65   886.4 2009.45
#Mann= 5 ,-1,0
       0     .05       0   329.6      .1       0     649    .045       0
   667.2      .1       0   847.8     .05       0
#XS Ineff= 2 , 0
       0     400    2007     767       0    2007
Permanent Ineff=
       F       F
Bank Sta=649,667.2
XS Rating Curve= 0 ,0
Exp/Cntr=0.3,0.1

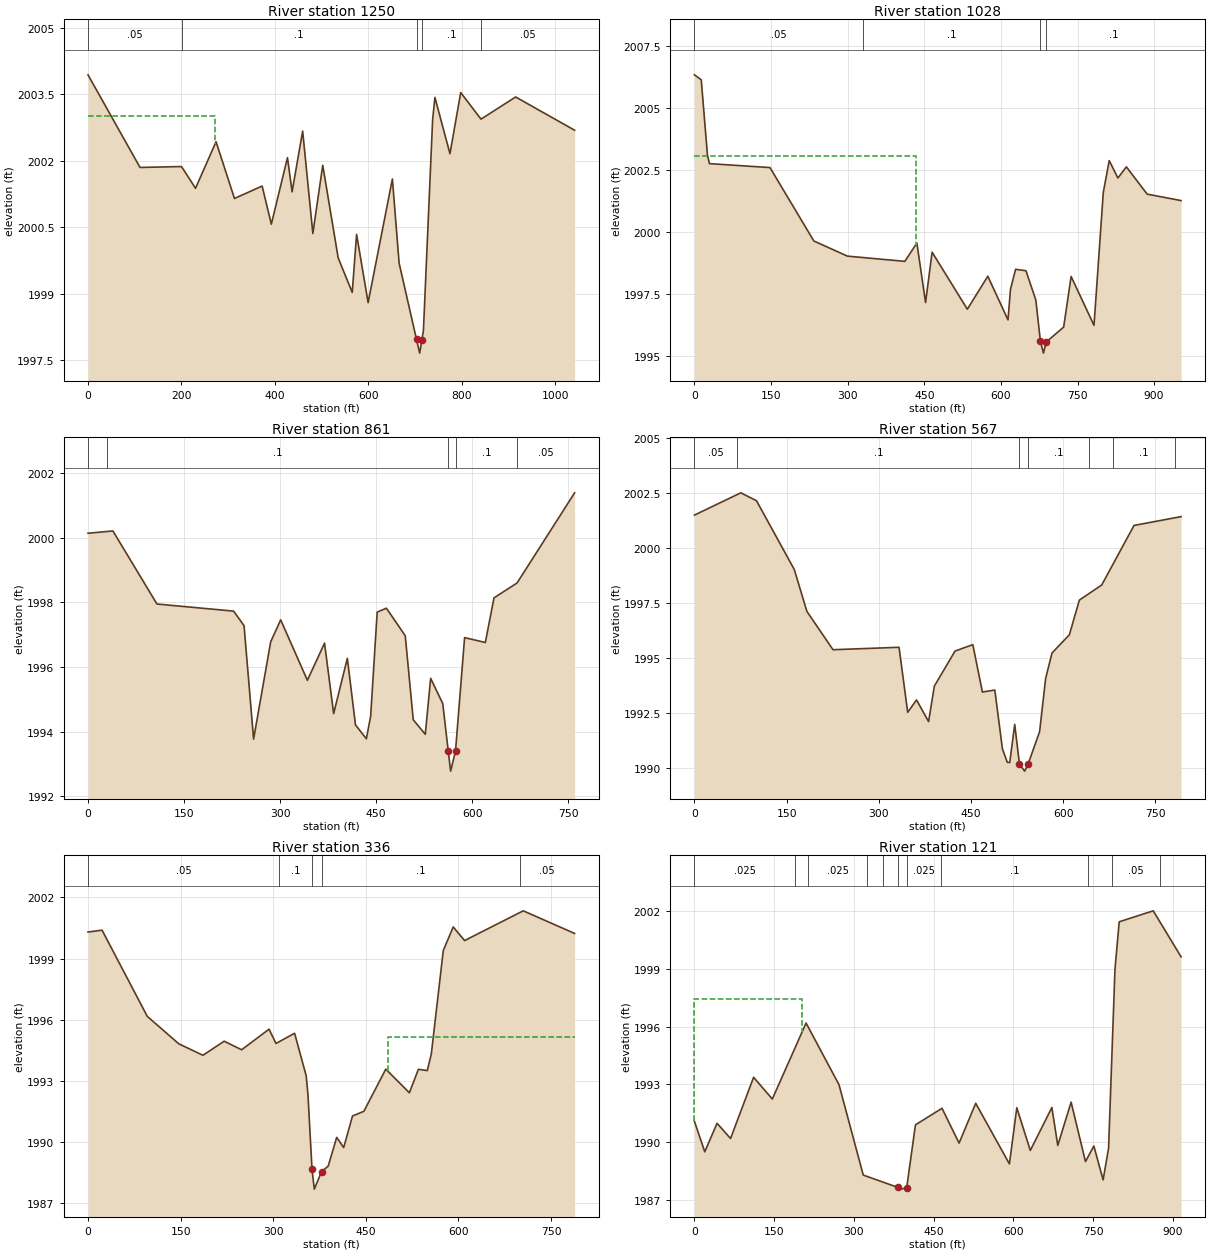
Type RM Length L Ch R = 1 ,1250    ,222.4,222.2,222.5
XS GIS Cut Line= 2
2190958.49717408389386.3157268732190113.71251117389994.913494472
#Sta/Elev= 30
       0 2003.94   111.3 2001.85   200.1 2001.87   230.1 2001.38     274 2002.43
   313.4 2001.15   372.6 2001.43   392.3 2000.57   426.8 2002.07   436.7  2001.3
   459.3 2002.67   481.1 2000.36   502.3  2001.9   535.3 1999.81   565.4 1999.03
   574.7 2000.34   599.4  1998.8   651.3 2001.59   665.7 1999.69   702.9 1997.97
   709.7 1997.66   714.4 1997.96   717.7 1998.17   737.4 2002.93   742.3 2003.43
   774.5 2002.16   797.5 2003.54   840.9 2002.94     915 2003.44  1041.2 2002.69
#Mann= 5 ,-1,0
       0     .05       0   200.1      .1       0   702.9    .045       0
   714.4      .1       0   840.9     .05       0
#XS Ineff= 2 , 0
           271.8    2003
Permanent Ineff=
       F       F
Bank Sta=702.9,714.4
XS Rating Curve= 0 ,0
Exp/Cntr(USF)=0,0
Exp/Cntr=0.3,0.1

Type RM Length L Ch R = 1 ,1028    ,169.7,167,168.5
XS GIS Cut Line= 2
2190879.79715032389194.1467287712190110.59220264389756.339759113
#Sta/Elev= 30
       0 2006.34    13.3 2006.14    25.5 2003.09    29.3 2002.76   147.9  2002.6
   233.8 1999.64   299.6 1999.03   411.9 1998.82   435.5 1999.56   452.5 1997.16
   465.3 1999.19   534.3 1996.89   574.4 1998.22   613.9 1996.46   618.8  1997.7
   628.8  1998.5   649.1 1998.44   668.4 1997.26677.31151995.615   683.3 1995.12
688.81131995.569   722.9 1996.17   737.5 1998.21   782.3 1996.24   800.5  2001.6
   812.1 2002.88   829.1 2002.18   845.7 2002.63   886.4 2001.53   952.8 2001.27
#Mann= 4 ,-1,0
       0     .05       0     330      .1       0677.3115    .045       0
688.8113      .1       0
#XS Ineff= 2 , 0
          433.18 2003.06
Permanent Ineff=
       F       F
Bank Sta=677.3115,688.8113
XS Rating Curve= 0 ,0
Exp/Cntr=0.3,0.1

Type RM Length L Ch R = 1 ,861     ,288.8,294,300.1
XS GIS Cut Line= 2
2190615.48716014389192.2700618422190031.39010782389678.364253032
#Sta/Elev= 30
       0 2000.14    38.9 2000.21   107.7 1997.95   227.4 1997.73   243.7 1997.28
   258.6 1993.77   285.3 1996.78   300.9 1997.46   342.6 1995.59   369.4 1996.74
   383.6 1994.56     405 1996.27   417.7 1994.21   434.7 1993.78   441.4 1994.48
   451.6  1997.7     466 1997.82   495.4 1996.97   507.9 1994.37   526.7 1993.92
   535.1 1995.65     554 1994.87   562.5 1993.41   566.3 1992.78   573.9  1993.4
   588.1 1996.91   620.5 1996.76     634 1998.14     670  1998.6   759.9 2001.39
#Mann= 5 ,-1,0
       0     .05       0      30      .1       0   562.5    .045       0
   573.9      .1       0     670     .05       0
Bank Sta=562.5,573.9
XS Rating Curve= 0 ,0
Exp/Cntr(USF)=0,0
Exp/Cntr=0.3,0.1

Type RM Length L Ch R = 1 ,567     ,238.2,231,222
XS GIS Cut Line= 3
2190549.20379693388947.4256469042190258.75674564389253.031835741
2189892.38424096  389308.2663378
#Sta/Elev= 30
       0 2001.49    75.5  2002.5     101 2002.14   162.5 1999.02     183 1997.12
   225.5 1995.38     333 1995.49   347.1 1992.54   361.5  1993.1   381.1 1992.12
   390.5 1993.73   424.2 1995.32   453.1 1995.61   468.7 1993.46   488.9 1993.55
   501.3 1990.88   509.2 1990.27   513.2 1990.26   521.3 1991.99 529.077 1990.18
   537.5 1989.87 543.077 1990.19   561.8 1991.66   571.6 1994.07     582 1995.23
   610.3 1996.06   626.5 1997.63     663 1998.32   715.5 2001.02   792.1 2001.42
#Mann= 7 ,-1,0
       0     .05       0      70      .1       0 529.077    .045       0
 543.077      .1       0  641.61     .05       0  681.61      .1       0
  781.61     .05       0
Bank Sta=529.077,543.077
XS Rating Curve= 0 ,0
Exp/Cntr=0.3,0.1

Type RM Length L Ch R = 1 ,336     ,211.6,215,210
XS GIS Cut Line= 3
2190424.38158094388785.5581881652190069.61122366389137.388459611
2189831.46427112389300.073209082
#Sta/Elev= 30
       0  2000.3    22.8 2000.39      96 1996.16   147.2 1994.81   186.2 1994.25
   220.5 1994.94   248.8 1994.52   293.2 1995.53   304.5 1994.83   334.6 1995.33
   353.4 1993.24   356.3 1992.29   362.81988.656   366.5 1987.68   378.3 1988.54
     389 1988.81   402.8 1990.22   414.1 1989.72   428.4 1991.27   446.8  1991.5
   482.3 1993.57   520.5 1992.41   535.1 1993.56   549.5  1993.5     556 1994.31
   575.4 1999.39   591.5 2000.55   609.9 1999.88   704.9 2001.34   788.1 2000.23
#Mann= 5 ,-1,0
       0     .05       0     310      .1       0   362.8    .045       0
   378.3      .1       0  699.65     .05       0
#XS Ineff= 2 , 0
                          485.86         1995.15
Permanent Ineff=
       F       F
Bank Sta=362.8,378.3
XS Rating Curve= 0 ,0
Exp/Cntr(USF)=0,0
Exp/Cntr=0.3,0.1

Type RM Length L Ch R = 1 ,121     ,,,
XS GIS Cut Line= 5
2190227.31186363388641.2392225392190105.59861592388817.871862506
2189891.85827848389022.7063525522189682.57086474389185.980221429
2189687.02378844389325.505163923
#Sta/Elev= 30
       0 1991.08    19.4  1989.5    42.5 1990.98    67.9 1990.19   111.3 1993.37
   146.5 1992.24     210 1996.19   271.9 1992.99   317.6 1988.29   382.7 1987.65
   388.2 1987.56   399.3 1987.63   415.8  1990.9   465.8 1991.76   497.9 1989.95
   529.2 1992.02   592.6 1988.87   606.5 1991.79   631.9 1989.57   672.5  1991.8
   683.6 1989.83   708.7 1992.08   735.7 1988.99   751.5  1989.8   768.9 1988.04
   779.2 1989.69   791.2 1998.98   799.2 2001.45   863.2 2002.02   915.6 1999.63
#Mann= 11 ,-1,0
       0    .025       0     190      .1       0  214.51    .025       0
  324.51      .1       0  354.51    .025       0   382.7    .045       0
   399.3    .025       0  464.51      .1       0  740.55    .025       0
  785.99     .05       0  875.99      .1       0
#XS Ineff= 2 , 0
          202.76 1997.45
Permanent Ineff=
       F       F
Bank Sta=382.7,399.3
XS Rating Curve= 0 ,0
Exp/Cntr(USF)=0,0
Exp/Cntr=0.3,0.1
LCMann Table=0

Chan Stop Cuts=-1
Use User Specified Reach Order=0
Composite Channel Slope=5